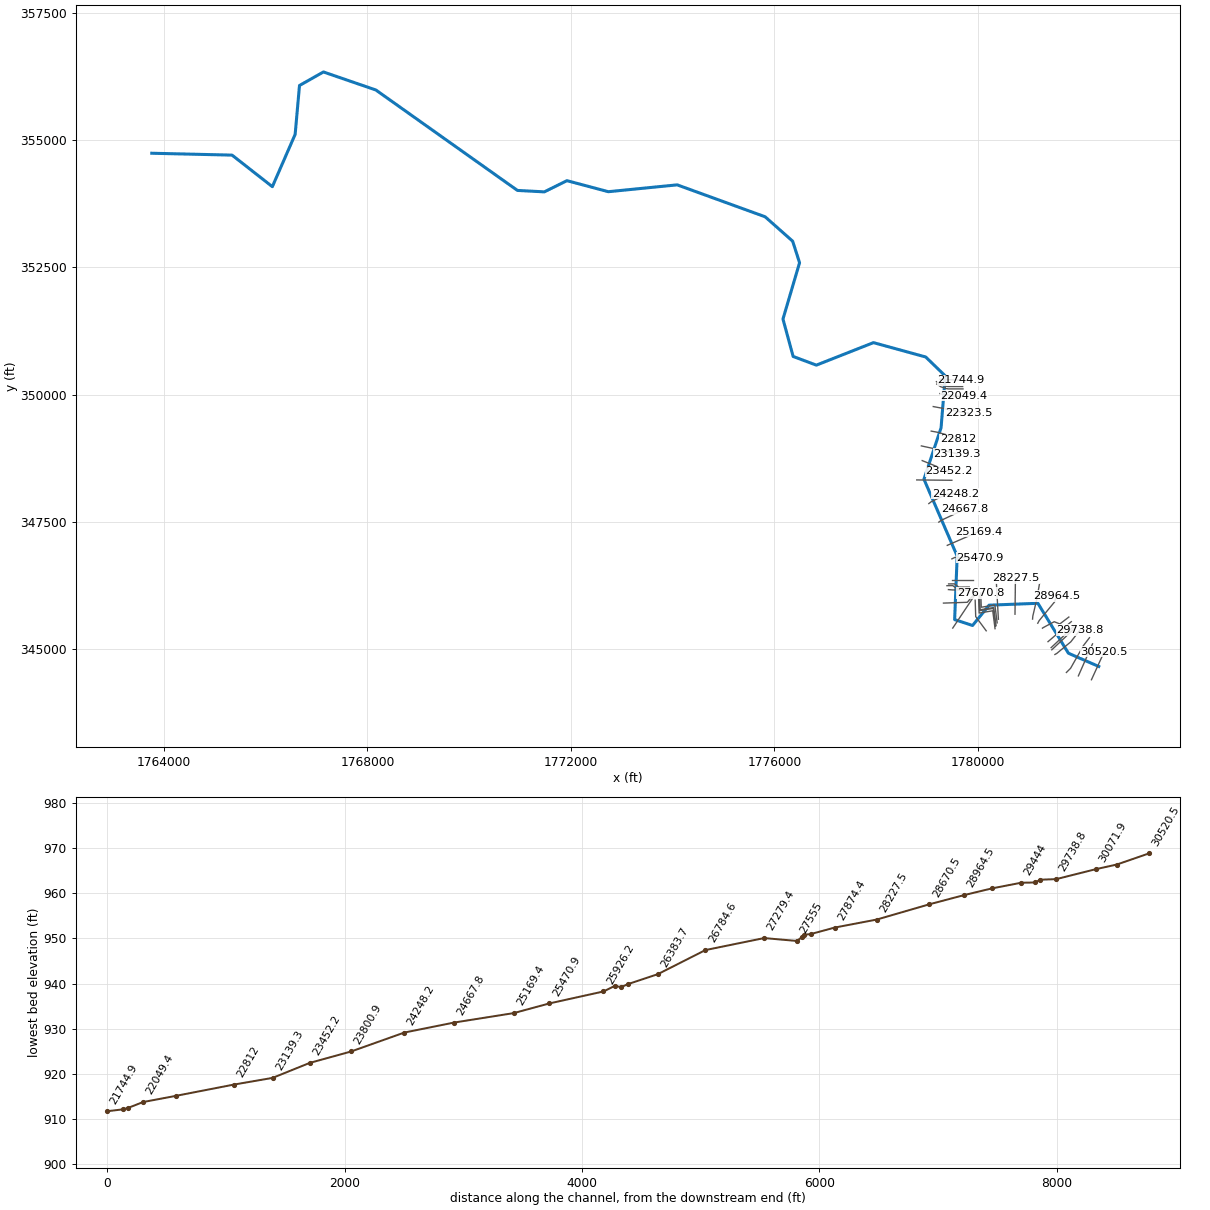
--- WESTFK.prj (project) ---

Proj Title=WESTFK
Current Plan=p01
Default Exp/Contr=0,0
English Units
Geom File=g01
Flow File=f01
Plan File=p01
BEGIN DESCRIPTION:
END DESCRIPTION:
DSS Export Rating Curves= 0
DSS Export Rating Curve Sorted= 0
DSS Export Volume Flow Curves= 0
DXF OffsetX= 0
DXF OffsetY= 0
DXF ScaleX= 0
DXF ScaleY= 0

--- WESTFK.p01 (plan) ---

Plan Title=Floodplain
Program Version=4.00
Geom File=g01
Flow File=f01
K Sum by GR=0
Std Step Tol=0.01
Critical Tol=0.01
Num of Std Step Trials=20
Max Error Tol=0.3
Flow Tol Ratio=0.001
Split Flow NTrial=30
Split Flow Tol=0.02
Split Flow Ratio=0.02
Log Output Level=0
Friction Slope Method=1
Unsteady Friction Slope Method=2
Unsteady Bridges Friction Slope Method=1
Global Log Level=0
CheckData=False
Run HTab=0
Run UNet=0
Run PostProcess=0
UNET Theta=0
UNET Theta Warmup=0
UNET ZTol=0
UNET ZSATol=0
UNET MxIter=0
UNET MaxInSteps=0
UNET DtIC=0
UNET DtMin=0
UNET MaxCRTS=0
UNET WFStab=0
UNET SFStab=0
UNET WFX=0
UNET SFX=0
UNET DSS MLevel=0
UNET DZMax Abort=0
UNET Convert EG Bridges=0
UNET Use Existing IB Tables=0
UNET Froude Limit=0
UNET Froude Power=0
Write IC File=0
Echo Input=False
Echo Output=False
Write Detailed=0

--- WESTFK.f01 (steady flow) ---

Flow Title=NFF Regression Equation
Program Version=4.00
Number of Profiles=1
Profile Names=P100yr
River Rch & RM=WESTFK,Main      ,30520.5
4893.090
River Rch & RM=WESTFK,Main      ,25470.9
4989.837
River Rch & RM=WESTFK,Main      ,15493.8
5541.900
River Rch & RM=WESTFK,Main      ,5751.3
5847.633
River Rch & RM=WESTFK,Main      ,5018.8
6627.836
River Rch & RM=WESTFK,Main      ,581.6
6995.254
Boundary for River Rch & Prof#=WESTFK,Main      ,1
Up Type=0
Dn Type=3
Dn Slope=0.006817

--- WESTFK.g01 (geometry) ---

Geom Title=USGS 10m DEM
Program Version=4.10

River Reach=WESTFK          ,Main
Reach XY= 30
     1782380.216      344653.101       1781783.3      344913.374
     1781183.256      345895.362     1780224.055       345858.47
     1779898.534      345459.164     1779546.015      345574.542
     1779595.928      346824.651     1778942.716      348335.609
     1779279.088      349346.352      1779362.51      350365.848
     1778976.934      350738.846     1777949.749       351021.23
     1776826.702      350578.522     1776370.234      350749.325
     1776170.235      351484.555     1776496.536      352592.294
     1776361.119      353015.341     1775819.452      353495.809
     1774090.287      354123.693     1772736.121      353989.144
     1771921.234      354206.158     1771478.525      353985.889
     1770949.011      354014.101     1768164.504      355989.299
     1767133.907      356343.745     1766663.036      356077.598
     1766577.436      355115.905     1766129.133      354087.886
     1765337.032      354708.545     1763758.256      354745.438

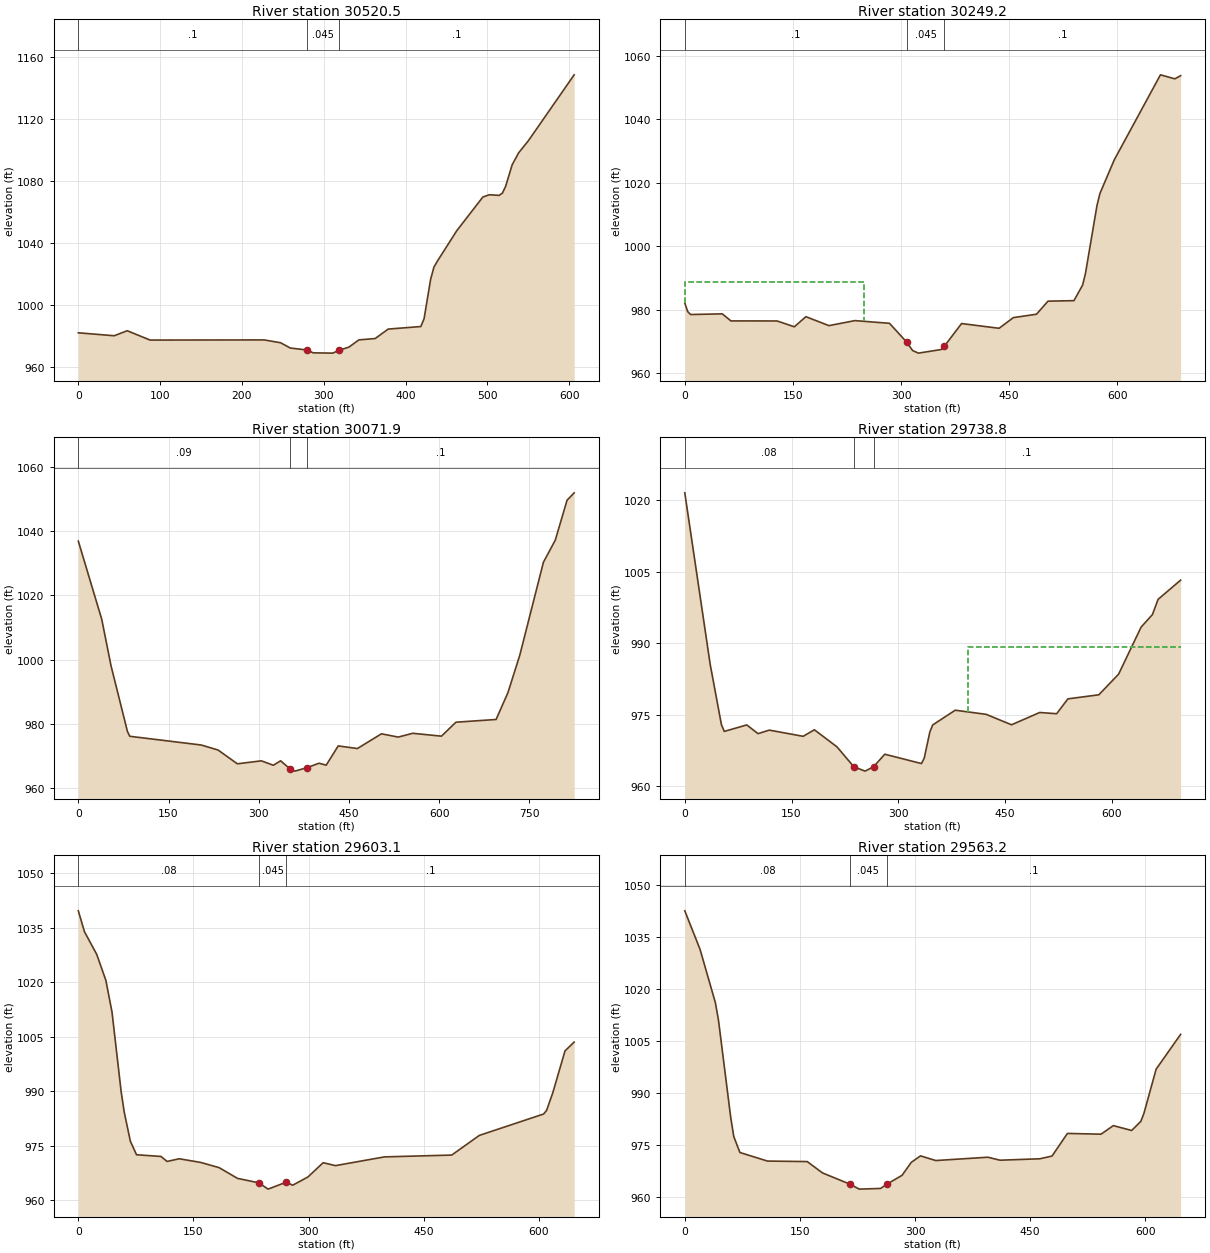
Type RM Length L Ch R = 1 ,30520.5 ,271.1,271.3,271.5
XS GIS Cut Line= 2
     1782236.323      344391.976     1782488.059      344943.192
#Sta/Elev= 30
       0  981.97    43.8  980.07    59.8   983.3    87.7  977.28   227.2  977.37
   247.2  975.54   259.1  972.13   279.1   970.9     287  969.02     311  968.84
   318.9  970.69   330.9  972.78   342.9  977.39   362.8  978.27   378.7  984.37
   418.6  986.02   422.6  991.13   430.6 1016.56   434.6 1024.38   438.5 1027.98
   462.5 1047.91   494.4 1069.68   502.3 1071.16   514.3 1070.76   518.3 1072.21
   522.3 1076.68   530.2 1090.48   538.2 1098.28   550.2 1106.17     606 1148.65
#Mann= 3 , 0 , 0
       0      .1       0   279.1    .045       0   318.9      .1       0
Bank Sta=279.1,318.9
XS Rating Curve= 0 ,0
Exp/Cntr=0.3,0.1

Type RM Length L Ch R = 1 ,30249.2 ,179.5,177.3,175.1
XS GIS Cut Line= 2
     1781979.254      344467.914     1782257.032      345097.254
#Sta/Elev= 30
       0  982.13       4  979.46       8  978.53      52  978.74      64  976.52
     128   976.5     152  974.67     168  977.85     200  975.03     236  976.61
     284  975.76     308  969.79     316   967.2     324  966.37     356  967.51
     360  968.51     384  975.69     436  974.19   455.9  977.56   487.9  978.62
   503.9  982.74   539.9   982.9   551.9  987.79   555.9   991.5   571.9 1012.91
   575.9 1016.63   595.9 1027.27   659.9 1054.03   679.9 1052.77   687.9 1053.76
#Mann= 3 , 0 , 0
       0      .1       0     308    .045       0     360      .1       0
#XS Ineff= 2 , 0
          249.25  988.83
Permanent Ineff=
       F       F
Bank Sta=308,360
XS Rating Curve= 0 ,0
Exp/Cntr=0.3,0.1

Type RM Length L Ch R = 1 ,30071.9 ,340.4,333.1,324.1
XS GIS Cut Line= 4
     1781743.702      344535.206     1781826.167      344617.671
     1782077.903      345062.549     1782197.261      345218.799
#Sta/Elev= 30
       0 1036.89    38.9  1012.6    54.4   998.1    81.6  977.72    85.5  976.18
   204.5  973.46   232.4   971.9   264.4  967.62   304.3  968.54   324.3  967.17
   336.3  968.55   352.2  966.01   360.2  965.34   380.2  966.41   400.2   967.8
   412.1  967.19   432.1  973.18     464  972.37     504  976.95   531.9  975.93
   555.9  977.11   603.8  976.22   627.8  980.56   694.6  981.41   714.3  989.76
     734 1001.41   773.3 1030.33     793  1037.2   812.6 1049.63   824.4 1051.93
#Mann= 3 , 0 , 0
       0     .09       0   352.2    .045       0   380.2      .1       0
Bank Sta=352.2,380.2
XS Rating Curve= 0 ,0
Exp/Cntr=0.3,0.1

Type RM Length L Ch R = 1 ,29738.8 ,134.2,135.8,136.8
XS GIS Cut Line= 4
     1781517.573      344888.938     1781552.296      344908.035
     1781830.073      345137.202     1782012.365      345371.577
#Sta/Elev= 30
       0 1021.57    35.7  985.54    51.5  972.88    55.5  971.48    87.1  972.84
   102.9  971.01   118.8  971.75   166.3  970.45   182.1  971.82   213.8  968.24
   237.5  964.06   253.3  963.14   265.2  964.05     281  966.69   332.5  964.73
   336.4  965.84   344.3  971.34   348.3  972.83     380  975.93   423.5  975.06
   459.1  972.87   498.7  975.45   522.5  975.19   538.3  978.31   581.8  979.17
   609.6  983.51   641.2  993.38   657.1  996.01     665   999.2   696.7 1003.24
#Mann= 3 , 0 , 0
       0     .08       0   237.5    .045       0   265.2      .1       0
#XS Ineff= 2 , 0
                          397.43           989.2
Permanent Ineff=
       F       F
Bank Sta=237.5,265.2
XS Rating Curve= 0 ,0
Exp/Cntr=0.3,0.1

Type RM Length L Ch R = 1 ,29603.1 ,39.9,39.9,39.9
XS GIS Cut Line= 2
     1781456.809      344980.952     1781927.296       345423.66
#Sta/Elev= 30
       0 1039.67       8 1033.91    23.9 1027.71    35.9 1020.51    43.9 1011.75
    55.8  989.83    59.8  984.23    67.8  976.21    75.8  972.48   107.7  972.01
   115.6  970.64   131.6  971.37   159.5  970.36   183.4  968.93   207.4  965.97
   235.3  964.74   247.2  963.01   271.2  964.95   279.2  964.08   299.1  966.35
     319  970.29     335  969.48   398.8  971.89   486.5  972.39   522.4   977.8
   606.2   983.7   610.1  984.71   618.1   989.5   634.1  1001.1     646 1003.51
#Mann= 3 , 0 , 0
       0     .08       0   235.3    .045       0   271.2      .1       0
Bank Sta=235.3,271.2
XS Rating Curve= 0 ,0
Exp/Cntr=0.3,0.1

Type RM Length L Ch R = 1 ,29563.2 ,119.8,119.2,117.7
XS GIS Cut Line= 2
     1781442.921      345022.619     1781913.407      345465.327
#Sta/Elev= 30
       0 1042.64    19.9 1031.52    39.9 1016.11    43.9 1011.09    59.8  983.13
    63.8  977.57    71.8  972.96   107.7  970.49   159.5  970.34   179.4  967.07
   215.3  963.82   227.3   962.4   255.2   962.6   263.2   963.8   283.1  966.39
   295.1  970.12   307.1  971.99     327  970.64   394.8   971.6   410.7  970.74
   462.6  971.15   478.5  971.94   498.5  978.46   542.3  978.24   558.3  980.71
   582.2  979.31   594.2  981.95   598.2  984.26   614.1  996.99     646 1007.02
#Mann= 3 , 0 , 0
       0     .08       0   215.3    .045       0   263.2      .1       0
Bank Sta=215.3,263.2
XS Rating Curve= 0 ,0
Exp/Cntr=0.3,0.1

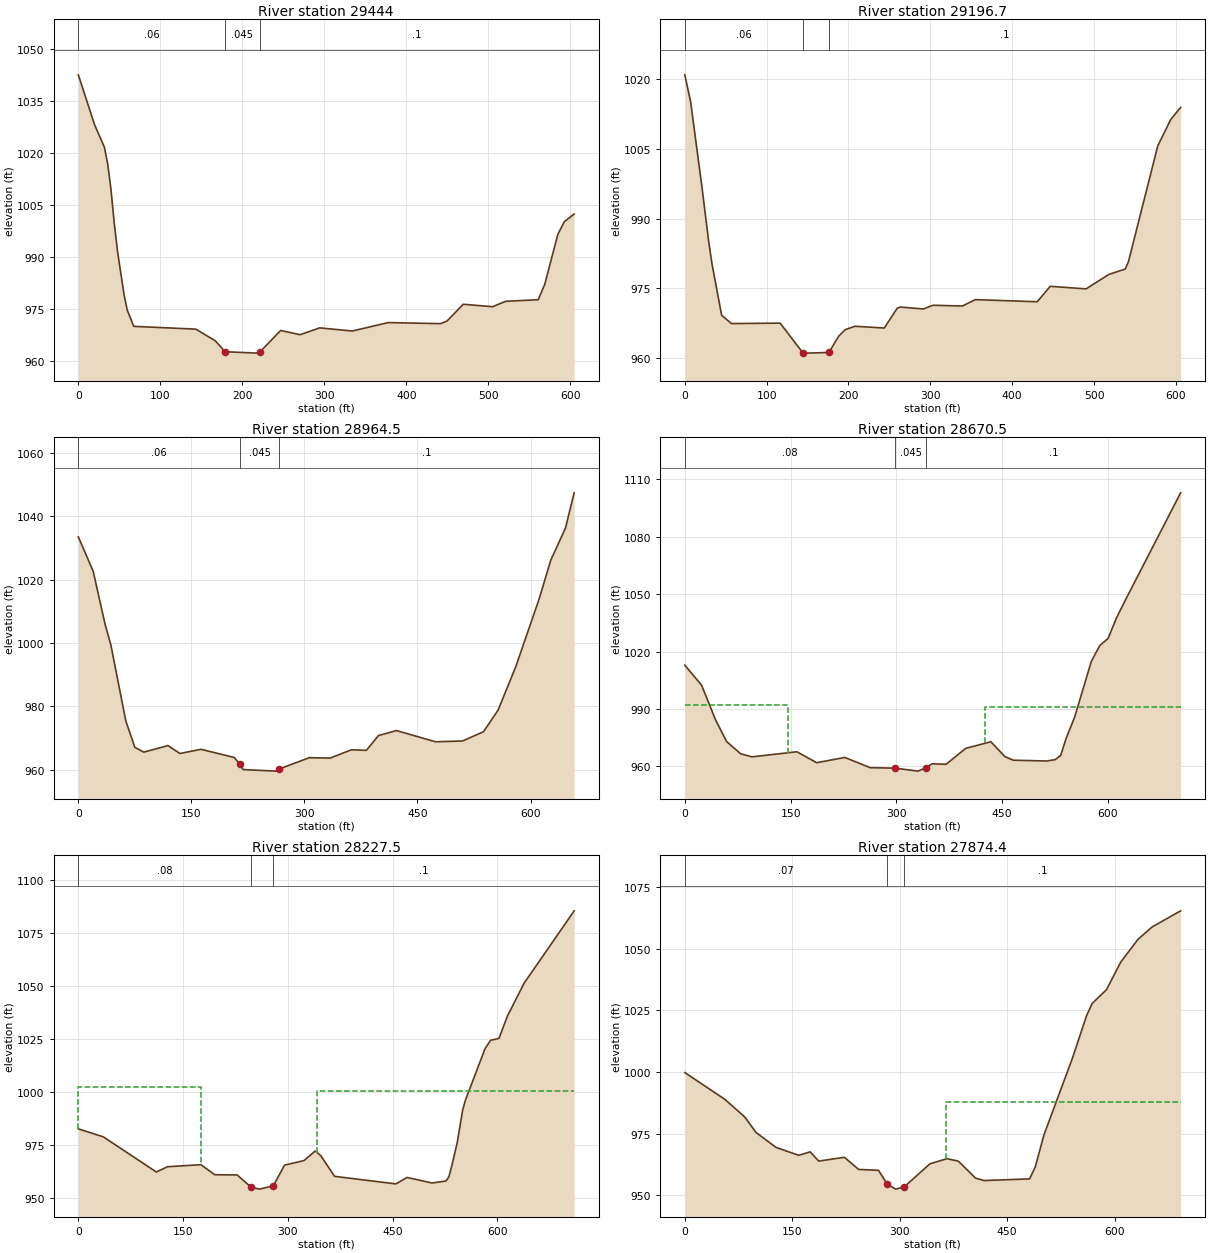
Type RM Length L Ch R = 1 ,29444   ,251.9,247.3,242.1
XS GIS Cut Line= 2
     1781382.157      345140.674      1781840.49      345534.772
#Sta/Elev= 30
       0  1042.6    19.9 1028.14    31.8 1021.71    35.8  1016.9    39.8 1009.54
    43.7 1000.03    47.7  991.84    55.7  979.26    59.6  974.78    67.6  970.06
   143.2  969.26     167  965.89     179  962.74   218.7  962.34     221 962.576
   246.6  968.87   270.4  967.66   294.3  969.62     334  968.72   377.8  971.15
   441.4  970.84   449.4  971.57   469.3  976.43     505  975.73     521  977.28
   560.7  977.75   568.7  982.22   584.6  996.59   592.5 1000.24   604.5 1002.46
#Mann= 3 , 0 , 0
       0     .06       0     179    .045       0     221      .1       0
Bank Sta=179,221
XS Rating Curve= 0 ,0
Exp/Cntr=0.3,0.1

Type RM Length L Ch R = 1 ,29196.7 ,221.5,232.2,242.3
XS GIS Cut Line= 5
     1781272.782      345406.299     1781290.143      345418.452
     1781503.684      345533.035     1781614.796      345489.633
     1781791.879      345625.049
#Sta/Elev= 30
       0 1020.94     7.1 1015.19    21.2  996.48    29.1   985.2    33.1  980.41
      45  969.23      57  967.44   116.5  967.53     144 961.213   148.3  961.08
   176.1  961.22     188  964.72     196  966.12   207.9  966.86   243.7  966.48
   259.6  970.76   263.5  970.99   291.4  970.58   303.3  971.38   339.1  971.21
     355  972.59   430.6  972.13   446.5  975.45   490.3   974.9   518.2  978.02
   538.1  979.16     542  980.71   577.9 1005.67   593.8 1011.35   605.8 1013.94
#Mann= 3 , 0 , 0
       0     .06       0     144    .045       0   176.1      .1       0
Bank Sta=144,176.1
XS Rating Curve= 0 ,0
Exp/Cntr=0.3,0.1

Type RM Length L Ch R = 1 ,28964.5 ,285,294,302.6
XS GIS Cut Line= 4
     1781180.768      345503.522     1781208.546      345555.605
     1781510.629      345921.924     1781548.823       346039.98
#Sta/Elev= 30
       0 1033.46    19.7 1022.62    35.4    1006    43.3  999.24      63  975.44
      75   967.1      87  965.59   118.9  967.67   134.8  965.17   162.8  966.49
   206.7  963.92   214.6  961.77   218.6   960.1   262.5  959.61   266.5  960.28
   306.4  963.84   334.3  963.73   362.3  966.34   382.2  966.16   398.2  970.82
   422.1  972.39     474  968.86   509.9  969.11   537.7  972.05   557.1  978.91
   580.4  992.52   611.4 1013.85   626.9 1026.11   646.3 1036.17   657.9 1047.33
#Mann= 3 , 0 , 0
       0     .06       0   214.6    .045       0   266.5      .1       0
Bank Sta=214.6,266.5
XS Rating Curve= 0 ,0
Exp/Cntr=0.3,0.1

Type RM Length L Ch R = 1 ,28670.5 ,409,443,419
XS GIS Cut Line= 4
     1781078.337      345585.119     1781083.546      345644.147
     1781159.934      345970.535     1781213.754      346274.355
#Sta/Elev= 30
       0 1012.91    23.7 1002.54    43.5  984.47    59.3     973    79.2  966.63
    95.2  965.02     159  967.68     187  961.96   226.9  964.71   262.8  959.37
   298.7   959.1   330.6  957.56   342.6   959.4   350.6  961.37   370.5  961.15
   398.4  969.47     434  972.91   453.8  965.17   465.7  963.27   513.1  962.85
     525  963.55   532.9  965.73   540.8  974.81   552.7  985.75   576.4 1014.92
   588.3 1023.11   600.2 1026.92     612 1037.56   623.9 1046.38     703 1102.98
#Mann= 3 , 0 , 0
       0     .08       0   298.7    .045       0   342.6      .1       0
#XS Ineff= 2 , 0
          146.68  991.89  425.86           991.2
Permanent Ineff=
       F       F
Bank Sta=298.7,342.6
XS Rating Curve= 0 ,0
Exp/Cntr=0.3,0.1

Type RM Length L Ch R = 1 ,28227.5 ,351.2,353.1,354.2
XS GIS Cut Line= 2
     1780732.851      345680.605     1780741.532      346390.674
#Sta/Elev= 30
       0  982.58    35.9  978.79   111.7  962.25   127.7  964.72   175.5   965.7
   195.5  960.96   227.4  960.86   247.4  955.11   259.3  954.18   279.3  955.72
   295.2  965.48   323.2  967.62   339.1  972.11   347.1  970.02     367   960.2
   454.8  956.65   470.8  959.68   506.7  957.07   526.6  958.01   530.6  959.94
   534.6  964.79   542.6  976.02   550.5  991.53   554.5   996.2   582.5 1020.35
   590.4 1024.28   602.4 1025.16   614.4 1035.59   638.3 1051.11   710.1 1085.26
#Mann= 3 , 0 , 0
       0     .08       0   247.4    .045       0   279.3      .1       0
#XS Ineff= 2 , 0
          175.02 1002.45  342.25          1000.2
Permanent Ineff=
       F       F
Bank Sta=247.4,279.3
XS Rating Curve= 0 ,0
Exp/Cntr=0.3,0.1

Type RM Length L Ch R = 1 ,27874.4 ,53.1,203.6,244.7
XS GIS Cut Line= 2
     1780406.462      345581.647     1780368.268      346272.619
#Sta/Elev= 30
       0  999.78    55.7  988.94    83.5   981.8    99.4  975.45   127.3  969.37
   159.1  966.16     175  967.56   186.9   963.8   222.7  965.35   242.6  960.42
   270.4  960.05   282.4  954.48   294.3  952.41   306.2   953.3     342  962.68
   365.9  964.78   381.8  963.77   405.7  956.91   417.6   955.9   481.2  956.57
   489.2   961.5   501.1  974.31   540.9 1005.52   560.8 1022.95   568.7 1027.89
   588.6 1033.47   608.5 1044.69   632.4 1053.88   652.3 1058.95     692 1065.49
#Mann= 3 , 0 , 0
       0     .07       0   282.4    .045       0   306.2      .1       0
#XS Ineff= 2 , 0
                          363.95          987.86
Permanent Ineff=
       F       F
Bank Sta=282.4,306.2
XS Rating Curve= 0 ,0
Exp/Cntr=0.3,0.1

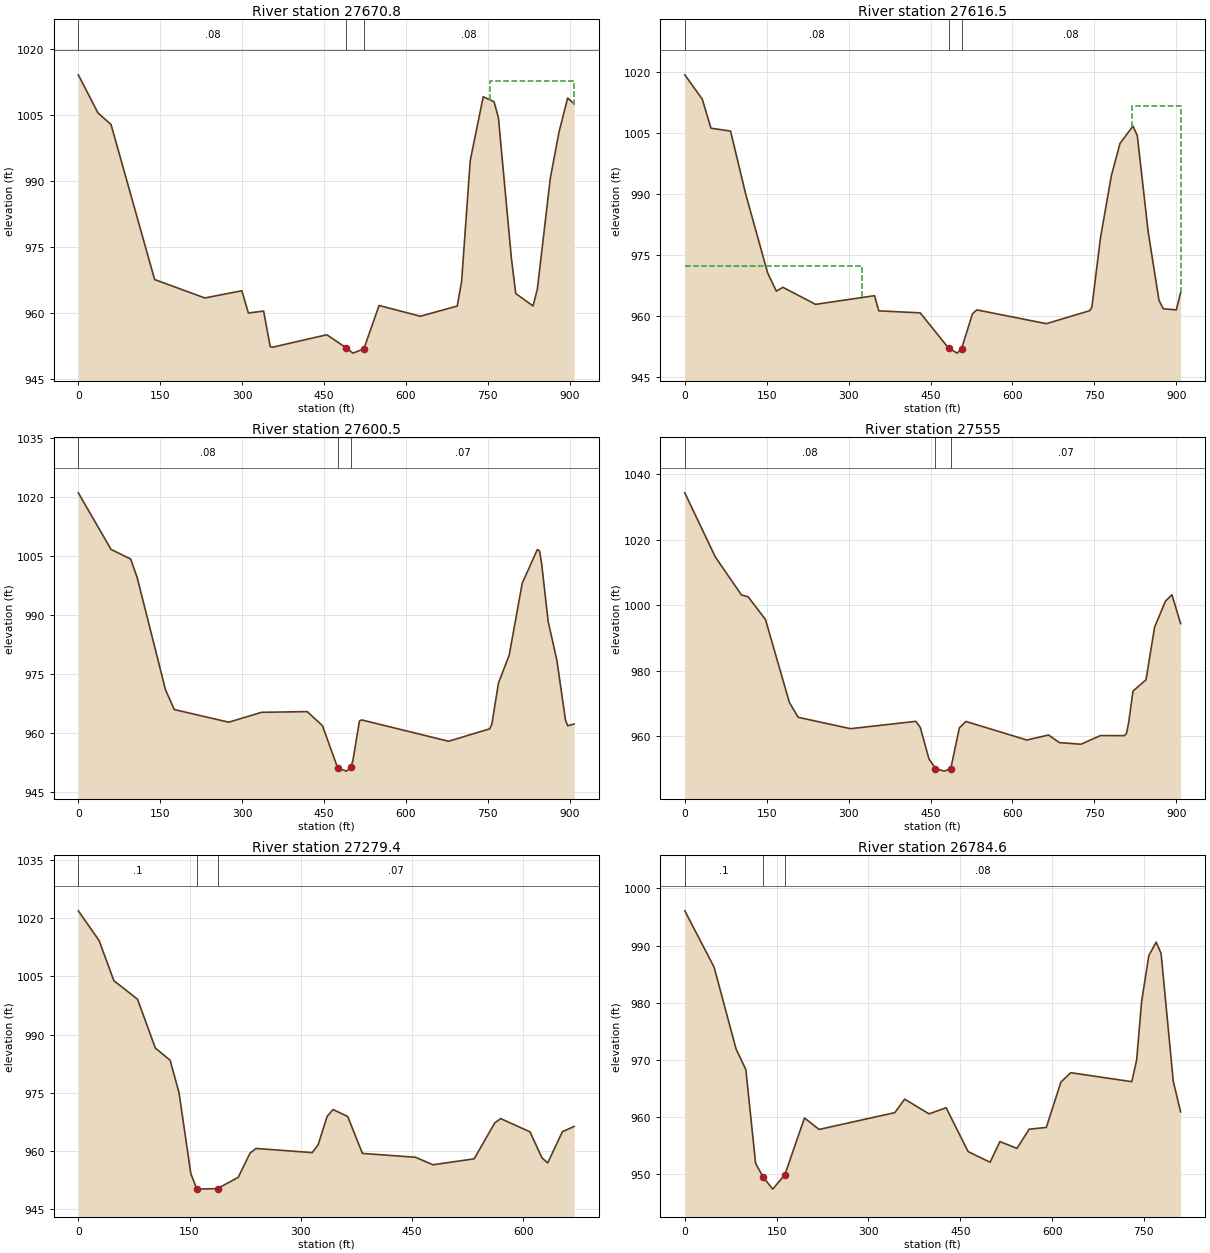
Type RM Length L Ch R = 1 ,27670.8 ,166.2,54.2,51.1
XS GIS Cut Line= 4
     1780382.157      345510.466     1780337.018      345862.897
     1780069.657      345817.758      1780059.24      346099.008
#Sta/Elev= 30
       0 1014.23    35.9 1005.58    59.9 1002.93   139.7  967.69   231.6   963.5
   299.4  965.14   311.4  960.08   339.3  960.52   351.3  952.47   355.3  952.29
     455  955.14   490.9  952.13   502.8  950.96   522.8  951.92   550.7  961.79
   626.4  959.34   693.8  961.67   701.8  967.23   717.6  994.73   741.4 1009.25
   761.2 1008.12   769.2 1004.49   792.9  972.64   800.9  964.52   832.6  961.68
   840.5  965.52   864.3  990.77   880.2 1001.24     896 1008.95   907.9 1007.64
#Mann= 3 , 0 , 0
       0     .08       0   490.9    .045       0   522.8     .08       0
#XS Ineff= 2 , 0
                          753.76         1012.77
Permanent Ineff=
       F       F
Bank Sta=490.9,522.8
XS Rating Curve= 0 ,0
Exp/Cntr=0.3,0.1

Type RM Length L Ch R = 1 ,27616.5 ,16,16,16
XS GIS Cut Line= 4
     1780359.587      345460.119     1780314.448      345812.549
     1780047.087       345767.41     1780036.671       346048.66
#Sta/Elev= 30
       0 1019.23    31.9 1013.28    47.9 1006.11    83.8  1005.4   111.8  989.76
   151.7  970.54   167.7  966.05   179.6     967   239.5  962.81   347.3  964.94
   355.3  961.21   431.1  960.72   482.9  952.07   498.9  950.82   506.8  951.92
   526.8   960.5   534.7  961.45   662.1  958.06   741.4  961.25   745.4  962.12
   761.2  979.18     781  994.39   796.9 1002.37   820.7 1006.64   828.6 1004.29
   848.4  980.71   868.3  963.77   876.2  961.73     900  961.45   907.9  965.71
#Mann= 3 , 0 , 0
       0     .08       0   482.9    .045       0   506.8     .08       0
#XS Ineff= 2 , 0
          324.18  972.32  819.31         1011.52
Permanent Ineff=
       F       F
Bank Sta=482.9,506.8
XS Rating Curve= 0 ,0
Exp/Cntr=0.3,0.1

Type RM Length L Ch R = 1 ,27600.5 ,45.5,45.5,45.5
XS GIS Cut Line= 4
     1780350.907      345442.758     1780305.768      345795.188
     1780038.407      345750.049      1780027.99      346031.299
#Sta/Elev= 30
       0    1021    59.9 1006.63    95.8  1004.2   107.8  999.47   159.7  970.97
   175.7  965.98   275.5  962.77   335.4  965.28   419.1  965.46     447   961.9
   474.9  951.16   490.9  950.35   498.9  951.31   502.8  953.07   514.8  963.08
   518.8  963.35     678  957.93   753.3  961.09   757.3  962.29   769.2  972.66
     789  979.82   812.8  998.05   840.5 1006.61   844.5 1006.28   848.4 1002.97
   860.3  988.34   876.2  978.56     892  963.34     896  961.86   907.9  962.31
#Mann= 3 , 0 , 0
       0     .08       0   474.9    .045       0   498.9     .07       0
Bank Sta=474.9,498.9
XS Rating Curve= 0 ,0
Exp/Cntr=0.3,0.1

Type RM Length L Ch R = 1 ,27555   ,300.6,275.6,251.4
XS GIS Cut Line= 4
      1780340.49      345395.883     1780295.351      345748.313
      1780027.99      345703.174     1780017.573      345984.424
#Sta/Elev= 30
       0 1034.23    55.9 1014.68   103.8 1003.11   115.8 1002.58   147.7  995.65
   191.6  970.36   207.6  965.84   303.4  962.37   423.1  964.61   431.1   962.8
     447  953.22     459  950.21   474.9  949.44   486.9  950.12   502.8  962.62
   514.8  964.57   626.4  958.92   666.1  960.44   685.9  958.13   725.6  957.64
   761.2  960.28   804.8  960.24   808.8  960.93   812.8  964.28   820.7  973.81
   844.5  977.28   860.3  993.32   880.2 1001.24     892 1003.18   907.9  994.39
#Mann= 3 , 0 , 0
       0     .08       0     459    .045       0   486.9     .07       0
Bank Sta=459,486.9
XS Rating Curve= 0 ,0
Exp/Cntr=0.3,0.1

Type RM Length L Ch R = 1 ,27279.4 ,521.9,494.8,465.8
XS GIS Cut Line= 3
     1780166.879      345354.216     1779960.282       345633.73
     1779949.865       345954.91
#Sta/Elev= 30
       0 1021.93      28 1014.26    47.9 1003.91    79.9   999.1   103.9   986.5
   123.8  983.37   135.8  975.02   151.8  954.06   159.8  950.12   163.8  950.08
   187.8  950.23   215.7  953.12   231.7  959.39   239.7  960.58   315.6  959.51
   323.6  961.59   335.6  968.86   343.6  970.62   363.4  968.84   383.3   959.3
   454.7  958.31   478.5  956.37     534   957.9   561.8  967.19   569.8  968.29
   609.4  964.86   625.3  958.21   633.2  956.84   653.1  964.92   668.9  966.26
#Mann= 3 , 0 , 0
       0      .1       0   159.8    .045       0   187.8     .07       0
Bank Sta=159.8,187.8
XS Rating Curve= 0 ,0
Exp/Cntr=0.3,0.1

Type RM Length L Ch R = 1 ,26784.6 ,422,400.9,379
XS GIS Cut Line= 2
     1779508.893      345408.035     1779958.546      346081.647
#Sta/Elev= 30
       0  996.09    47.9  986.23    83.8  971.92    99.7  968.33   115.7  951.92
   127.7  949.58   143.6  947.42   163.6  949.97   195.5  959.87   219.4  957.86
   343.1   960.8   359.1  963.16     399  960.58   426.9  961.65   462.8  953.98
   498.7  952.12   514.7  955.73   542.6  954.55   562.5   957.9   590.5  958.21
   614.4  966.15   630.4  967.78   730.1  966.21   738.1  970.02   746.1  980.16
     758  988.28     770  990.62     778  988.63   797.9  966.26   809.9  960.93
#Mann= 3 , 0 , 0
       0      .1       0   127.7    .045       0   163.6     .08       0
Bank Sta=127.7,163.6
XS Rating Curve= 0 ,0
Exp/Cntr=0.3,0.1

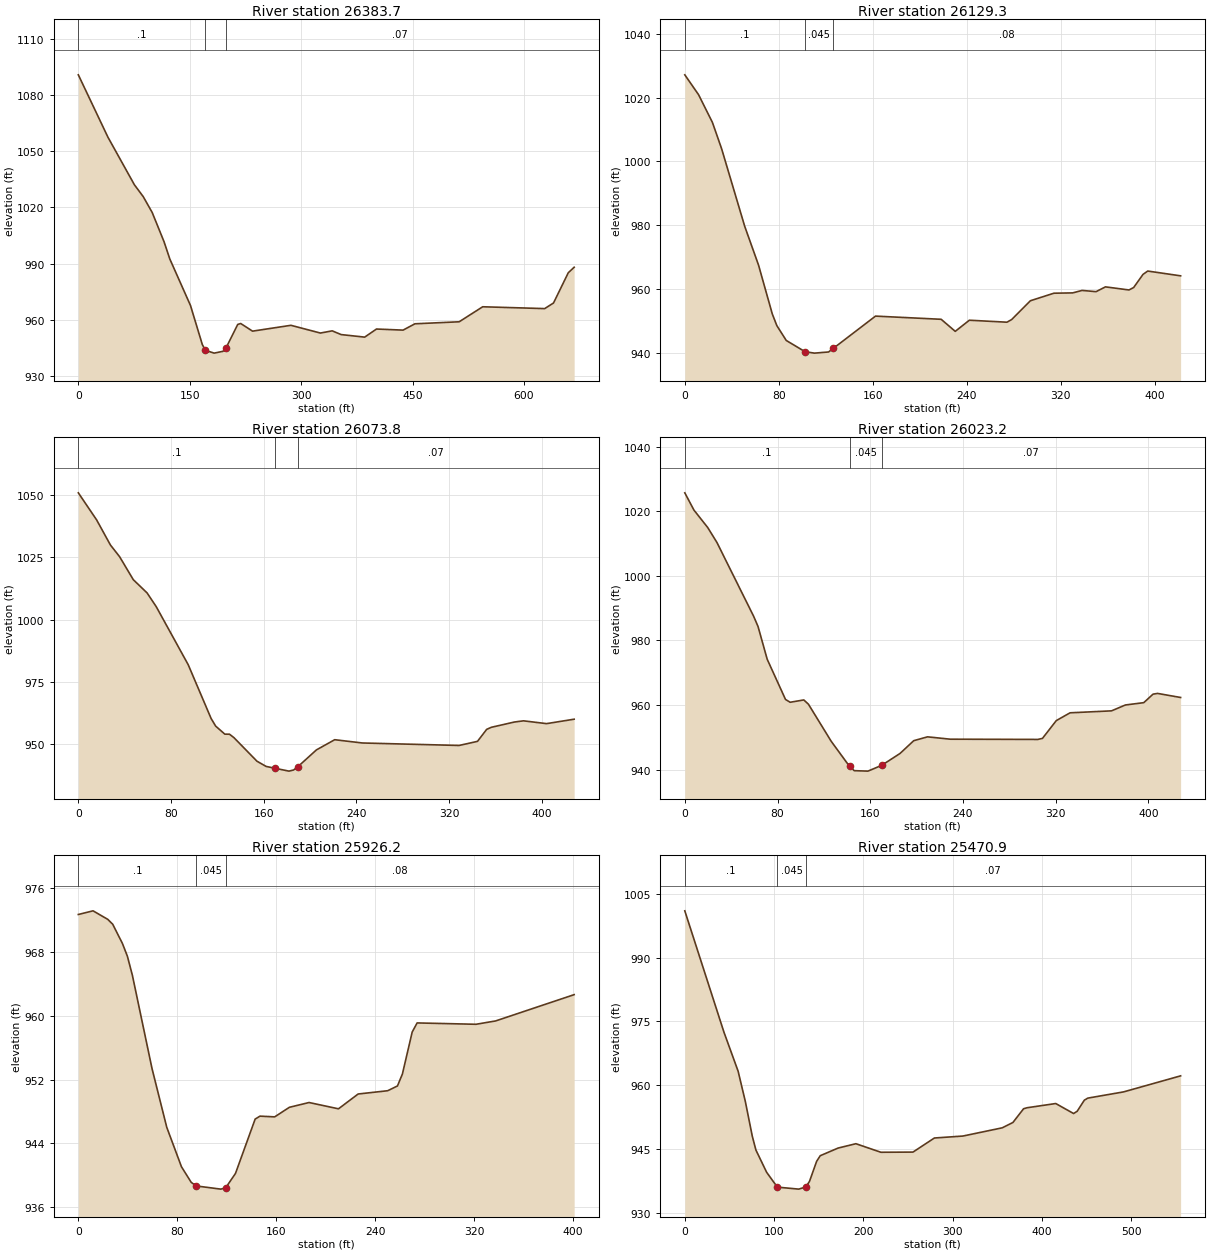
Type RM Length L Ch R = 1 ,26383.7 ,255.3,254.4,253.5
XS GIS Cut Line= 3
     1779326.601      345899.355     1779795.351       345914.98
     1779922.087      346067.758
#Sta/Elev= 30
       0 1090.97    39.8 1057.65    75.5 1032.14    87.4 1025.79    99.4 1017.36
   115.3 1001.77   123.2  992.41     151  967.56   166.9   946.7   170.9  943.62
   182.8  942.08   194.8  943.06   198.7  944.77   214.6  957.42   218.6  957.93
   234.5  953.84   286.2  956.96   325.9  952.82   341.8     954   353.8     952
   385.5  950.64   401.4  954.97   437.2  954.39   453.1  957.77   512.7  958.85
   544.4  966.88   627.8   965.9   639.7  968.89   659.6  985.09   667.5  988.02
#Mann= 3 , 0 , 0
       0      .1       0   170.9    .045       0   198.7     .07       0
Bank Sta=170.9,198.7
XS Rating Curve= 0 ,0
Exp/Cntr=0.3,0.1

Type RM Length L Ch R = 1 ,26129.3 ,69.6,55.5,41.4
XS GIS Cut Line= 3
     1779423.823       346164.98     1779501.948      346158.035
     1779845.698      346154.563
#Sta/Elev= 30
       0 1027.13    11.8 1020.86    23.5 1012.23    31.4  1003.9      51  979.64
    62.8  967.45    74.5  952.14    78.4  948.46    86.4  943.82   102.4   940.3
   110.4  939.85   122.4  940.21   126.4  941.32   162.4  951.46   218.3  950.46
   230.3  946.68   242.3  950.17   274.3  949.55   278.3  950.37   294.3  956.28
   314.3  958.64   330.3  958.74   338.3  959.51   350.2  959.13   358.2  960.63
   378.2  959.66   382.2  960.42   390.2  964.55   394.2  965.59   422.2  964.09
#Mann= 3 , 0 , 0
       0      .1       0   102.4    .045       0   126.4     .08       0
Bank Sta=102.4,126.4
XS Rating Curve= 0 ,0
Exp/Cntr=0.3,0.1

Type RM Length L Ch R = 1 ,26073.8 ,50.5,50.6,50.5
XS GIS Cut Line= 4
     1779394.309      346241.369     1779508.893      346243.105
     1779593.962      346178.869     1779800.559      346180.605
#Sta/Elev= 30
       0 1050.81    15.8 1039.94    27.7 1029.88    35.6  1025.2    47.4 1015.99
    59.3 1010.67    67.2 1005.17    94.8  981.87   114.6  960.26   118.5  957.25
   126.4  954.02   130.4     954   134.3   952.6   154.1  943.18     162  941.08
   169.9  940.32   181.7  939.19   185.7  939.64   189.6  941.04   205.4  947.69
   221.2  951.79     245  950.48   328.5  949.48   344.4  951.13   352.3  955.93
   356.3  956.76   376.2  958.88   384.1  959.36     404  958.24   427.8  960.02
#Mann= 3 , 0 , 0
       0      .1       0   169.9    .045       0   189.6     .07       0
Bank Sta=169.9,189.6
XS Rating Curve= 0 ,0
Exp/Cntr=0.3,0.1

Type RM Length L Ch R = 1 ,26023.2 ,81.3,97,112.1
XS GIS Cut Line= 4
     1779427.296      346276.091     1779541.879      346277.827
     1779626.948      346213.591     1779833.546      346215.327
#Sta/Elev= 30
       0 1025.71     7.9 1020.36    19.8 1014.95    27.7 1010.35    59.3  987.55
    63.2   984.3    71.1  974.16    86.9  961.71    90.9  960.84   102.7  961.56
   106.7  960.22   126.4  948.71   142.2  940.95   146.2  939.65     158  939.51
   169.9   941.3   185.7  944.98   197.5  948.93   209.4  950.13   229.1   949.4
   304.6  949.33   308.6  949.65   320.5  955.15   332.4  957.57   368.2  958.18
   380.1  959.99     396  960.72     404  963.35   407.9  963.58   427.8  962.32
#Mann= 3 , 0 , 0
       0      .1       0   142.2    .045       0   169.9     .07       0
Bank Sta=142.2,169.9
XS Rating Curve= 0 ,0
Exp/Cntr=0.3,0.1

Type RM Length L Ch R = 1 ,25926.2 ,456.1,455.3,454.8
XS GIS Cut Line= 2
      1779496.74      346343.799     1779897.782      346343.799
#Sta/Elev= 30
       0  972.72    11.9  973.18    23.8  972.11    27.8   971.5    35.7  969.07
    39.7  967.47    43.7   965.1    59.6  953.38    71.5  946.02    83.4  941.06
    91.3   939.1    95.3  938.65   115.2  938.25   119.1   938.4   127.1  940.22
     143  947.04   146.9  947.41   158.8  947.32   170.7  948.52   186.6  949.12
   210.4  948.33   226.3  950.19   250.2   950.6   258.1   951.2   262.1   952.7
     270  957.96     274  959.11   321.6  958.94   337.5  959.36     401  962.66
#Mann= 3 , 0 , 0
       0      .1       0    95.3    .045       0   119.1     .08       0
Bank Sta=95.3,119.1
XS Rating Curve= 0 ,0
Exp/Cntr=0.3,0.1

Type RM Length L Ch R = 1 ,25470.9 ,291.5,301.5,310.4
XS GIS Cut Line= 3
     1779491.532      346769.147     1779548.823      346796.924
     1780040.143      346793.452
#Sta/Elev= 30
       0 1000.98    43.8  972.49    59.7  963.29    67.7  956.25    75.6  947.99
    79.6  944.79    91.6  939.56   103.6  936.07   127.6   935.6   135.6  936.13
   139.6  937.43   147.6  942.14   151.6  943.45   171.5  945.24   191.5  946.27
   219.5  944.26   255.4   944.3   279.4  947.61   311.3  948.07   355.3     950
   367.3  951.26   379.2  954.48   383.2  954.72   415.2  955.71   435.2  953.36
   439.2  953.89   447.2  956.49   451.1  956.98   491.1  958.44     555  962.21
#Mann= 3 , 0 , 0
       0      .1       0   103.6    .045       0   135.6     .07       0
Bank Sta=103.6,135.6
XS Rating Curve= 0 ,0
Exp/Cntr=0.3,0.1

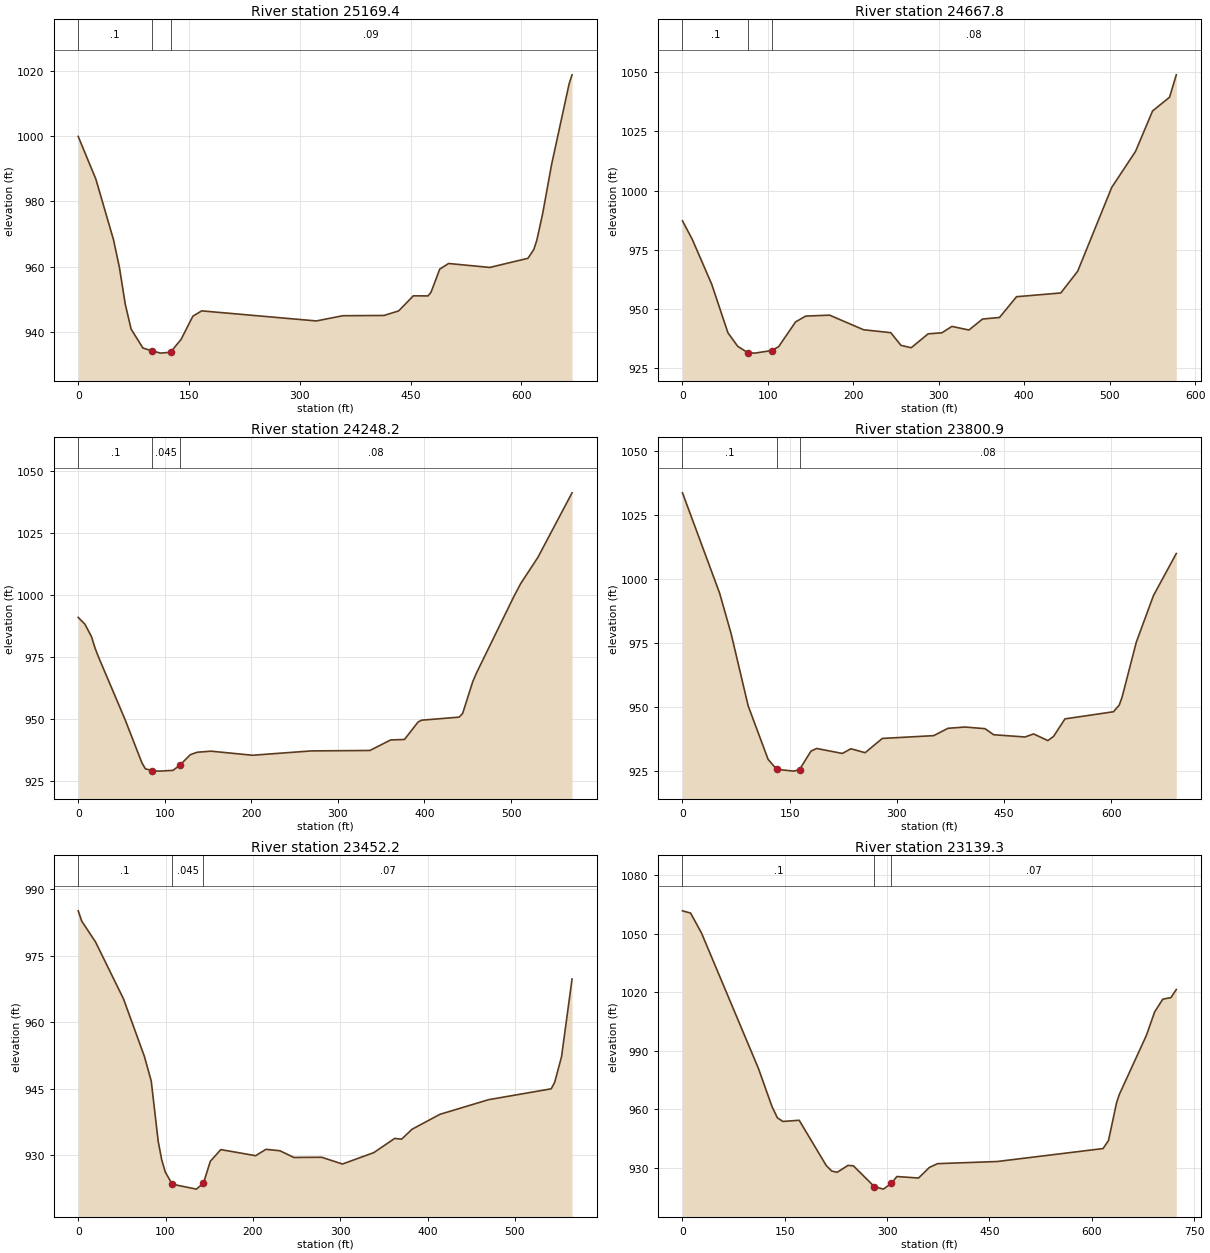
Type RM Length L Ch R = 1 ,25169.4 ,501.1,501.6,502.2
XS GIS Cut Line= 2
     1779401.254      347034.772     1780014.101      347302.133
#Sta/Elev= 30
       0   999.9    23.9   986.8    47.8   968.2    55.7   959.8    63.7  948.44
    71.6  940.82    87.6  935.01    99.5  934.18   111.4  933.45     125  933.72
   139.3  937.68   155.2  944.77   167.2  946.41   322.4  943.32   358.2  944.92
   413.9     945   433.8  946.39   453.7  951.02   473.6     951   477.6  952.09
   489.5  959.22   501.5  960.94   557.2  959.73   608.9  962.53   616.9  965.26
   620.9  968.06   628.8  976.21   640.8  991.19   664.6 1015.99   668.6  1018.8
#Mann= 3 , 0 , 0
       0      .1       0    99.5    .045       0     125     .09       0
Bank Sta=99.5,125
XS Rating Curve= 0 ,0
Exp/Cntr=0.3,0.1

Type RM Length L Ch R = 1 ,24667.8 ,418.5,419.5,419.5
XS GIS Cut Line= 3
     1779234.587      347491.369     1779283.198      347527.827
     1779751.948      347746.577
#Sta/Elev= 30
       0  987.18    11.4  979.44    34.2  960.46    53.2  939.95    64.7  934.21
    76.7  931.52    84.6  931.36   104.5  932.46   112.5  934.06   132.4  944.55
   144.3     947   172.2  947.39     212  941.22   243.8     940   255.7  934.65
   267.7  933.63   287.6  939.52   303.5  939.93   315.4  942.64   335.3  941.11
   351.2  945.75   371.1  946.42     391  955.18   442.8  956.76   462.6  965.95
   502.4 1001.31   530.3 1016.54   550.2 1033.58   570.1  1039.4     578 1048.85
#Mann= 3 , 0 , 0
       0      .1       0    76.7    .045       0   104.5     .08       0
Bank Sta=76.7,104.5
XS Rating Curve= 0 ,0
Exp/Cntr=0.3,0.1

Type RM Length L Ch R = 1 ,24248.2 ,458.1,447.3,436
XS GIS Cut Line= 4
     1779038.407      347855.952      1779090.49      347895.883
     1779373.476      348034.772     1779562.712      348046.924
#Sta/Elev= 30
       0  991.13     7.7  988.41    15.4  983.31    19.3   978.9    23.2  975.35
      54  950.03    73.6  932.46    77.6  930.07    85.6  929.34    93.6  929.14
   109.5  929.44   117.5  931.57   129.5  935.77   137.4  936.75   153.4  937.19
   201.3  935.54   269.1  937.29     337  937.47   360.9  941.71   376.9  941.91
   392.7  948.97   396.7  949.68   440.1  950.92   444.1  952.41   455.9  965.33
   459.9  968.58   503.3  999.57   511.2 1004.79     531 1015.31   570.5 1041.37
#Mann= 3 , 0 , 0
       0      .1       0    85.6    .045       0   117.5     .08       0
Bank Sta=85.6,117.5
XS Rating Curve= 0 ,0
Exp/Cntr=0.3,0.1

Type RM Length L Ch R = 1 ,23800.9 ,356.6,348.7,340.5
XS GIS Cut Line= 2
     1778800.559       348321.23     1779491.532      348314.285
#Sta/Elev= 30
       0 1033.68    51.9  994.54    67.9  978.82    91.9  950.48   119.8  929.55
   131.8  925.64   155.8  924.95   163.8  925.56   179.7  932.74   187.7   933.8
   223.7  931.86   235.7  933.69   255.6  932.15   279.6  937.72   351.5  938.81
   371.5  941.68   395.4  942.18   423.4  941.53   435.4  939.17   479.3  938.29
   491.3  939.48   511.3  936.89   519.2   938.5   535.2  945.36   603.1  948.15
   611.1  950.74   615.1  953.81   635.1   975.4     659  993.51     691 1009.98
#Mann= 3 , 0 , 0
       0      .1       0   131.8    .045       0   163.8     .08       0
Bank Sta=131.8,163.8
XS Rating Curve= 0 ,0
Exp/Cntr=0.3,0.1

Type RM Length L Ch R = 1 ,23452.2 ,308.6,312.9,316.5
XS GIS Cut Line= 2
     1778908.198      348701.438     1779432.504      348489.633
#Sta/Elev= 30
       0  985.15       4  982.84    19.9   978.1    51.8  965.32    75.7  952.38
    83.6   946.8    91.6  933.17    95.6  929.05    99.6  926.32   107.5  923.53
   135.4  922.42   143.4  923.77   151.3  928.71   163.3  931.33   203.1  929.96
     215  931.39     231  931.07   246.9  929.56   278.8   929.6   302.6  928.08
   338.5  930.65   362.4  933.85   370.3  933.68   382.3  935.92   414.2  939.28
   469.9  942.58   541.6  945.03   545.6  946.49   553.5  952.29   565.5  969.78
#Mann= 3 , 0 , 0
       0      .1       0   107.5    .045       0   143.4     .07       0
Bank Sta=107.5,143.4
XS Rating Curve= 0 ,0
Exp/Cntr=0.3,0.1

Type RM Length L Ch R = 1 ,23139.3 ,328.7,327.3,326
XS GIS Cut Line= 2
     1778891.147      348990.483     1779598.612      348836.404
#Sta/Elev= 30
       0 1061.79    11.9 1060.64    27.8 1050.46   111.4  980.94   131.3  961.37
   139.2  955.64   147.2   953.8   171.1   954.4   210.8   931.2   218.8  928.39
   226.8  927.74   242.7  931.26   250.6  931.04   281.2  920.43   294.4   919.1
   306.3  922.04   314.3  925.56   346.1  924.79     362  930.23     374  932.16
   461.5  933.26   616.6   939.9   624.6  944.04   636.5  963.48   640.5  967.66
   680.3  998.04   692.2 1009.94   704.2  1016.5   716.1 1017.28     724 1021.44
#Mann= 3 , 0 , 0
       0      .1       0   281.2    .045       0   306.3     .07       0
Bank Sta=281.2,306.3
XS Rating Curve= 0 ,0
Exp/Cntr=0.3,0.1

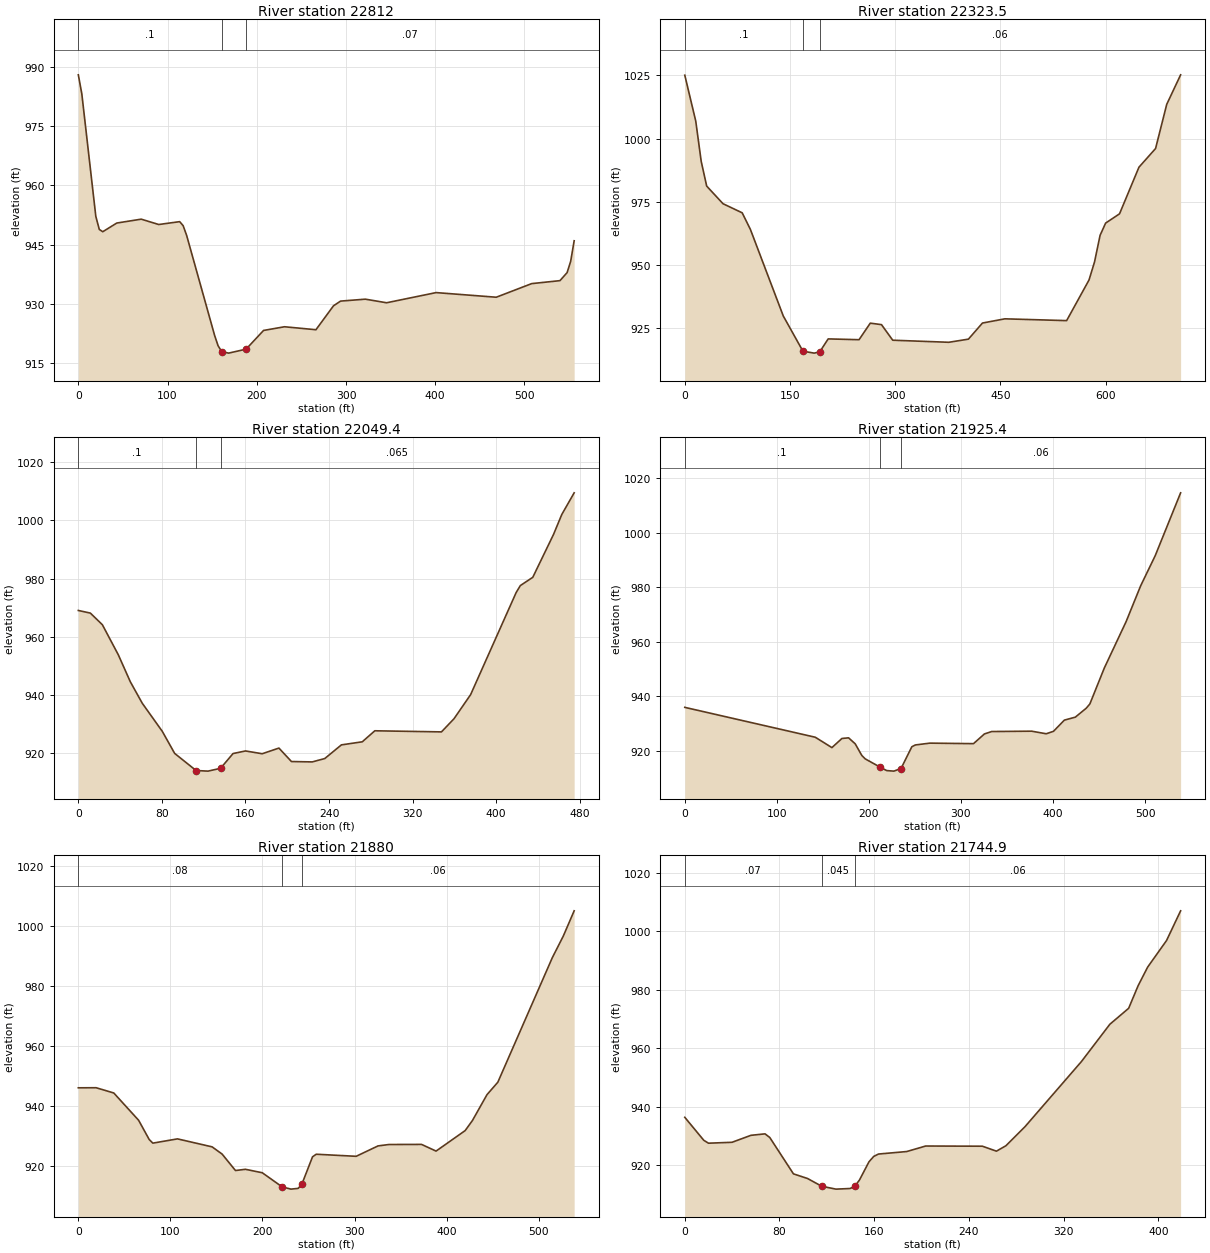
Type RM Length L Ch R = 1 ,22812   ,486.9,488.5,490
XS GIS Cut Line= 4
     1779085.282      349281.299     1779208.546       349258.73
     1779359.587      349217.063     1779614.796      349118.105
#Sta/Elev= 30
       0  987.91     3.9  983.12    19.6  952.15    23.5  948.85    27.4  948.28
    43.1  950.47    70.5  951.45    90.1   950.1   113.6  950.82   117.5   949.8
   121.4  947.34   152.7  922.12   156.6  919.49   160.6  918.01   168.4  917.61
     188  918.61   207.6  923.34   231.1  924.27   266.3  923.52     286  929.57
   293.9  930.75   321.7  931.24   345.5  930.33     401   932.9   468.4  931.73
   508.1  935.17   539.8  935.92   547.8  937.95   551.8   940.8   555.7  945.99
#Mann= 3 , 0 , 0
       0      .1       0   160.6    .045       0     188     .07       0
Bank Sta=160.6,188
XS Rating Curve= 0 ,0
Exp/Cntr=0.3,0.1

Type RM Length L Ch R = 1 ,22323.5 ,272,274.1,275.5
XS GIS Cut Line= 4
     1779125.212      349763.938     1779255.421      349739.633
     1779682.504      349652.827     1779819.657       349633.73
#Sta/Elev= 30
       0 1025.07    15.6 1006.94    23.4  990.97    31.2   981.2    54.5  974.22
    81.8  970.63    93.5  964.07   140.4   929.8   168.4  915.88   184.4  915.11
   192.4  915.62   204.4  920.74   248.4  920.42   264.4  926.97   280.4  926.38
   296.4  920.22   376.4   919.4   404.3  920.64   424.3  927.01   456.3  928.68
   544.3  927.97   576.2  944.03   584.1  951.21     592  961.72   599.9  966.56
   619.7  970.22   647.4  988.67   671.1  996.07     687 1013.54   706.8 1025.22
#Mann= 3 , 0 , 0
       0      .1       0   168.4    .045       0   192.4     .06       0
Bank Sta=168.4,192.4
XS Rating Curve= 0 ,0
Exp/Cntr=0.3,0.1

Type RM Length L Ch R = 1 ,22049.4 ,124.8,123.9,123.1
XS GIS Cut Line= 4
     1779257.157      350019.147     1779338.754      349998.313
     1779620.004      349963.591     1779725.907      349979.216
#Sta/Elev= 30
       0  969.03    11.5  968.13      23  964.13    38.3  953.76    49.8  944.47
    61.2  937.11    80.4  927.42    92.2  919.85   112.7  913.96   124.1  913.75
   136.1  914.71   148.1   919.8     160  920.69     176  919.73     192  921.68
     204  917.05   223.9  916.92   235.9  918.08   251.8  922.78   271.8  923.84
   283.8  927.63   347.6  927.25   359.6  931.78   375.5  940.07   419.1  975.21
   423.1   977.6     435  980.44   454.8  995.15   462.8 1002.08   474.6 1009.51
#Mann= 3 , 0 , 0
       0      .1       0   112.7    .045       0   136.1    .065       0
Bank Sta=112.7,136.1
XS Rating Curve= 0 ,0
Exp/Cntr=0.3,0.1

Type RM Length L Ch R = 1 ,21925.4 ,45.4,45.4,45.6
XS GIS Cut Line= 6
     1779194.657      350206.647     1779274.518      350152.827
     1779314.448      350140.674     1779368.268      350119.841
     1779422.087       350111.16     1779710.282       350111.16
#Sta/Elev= 30
       0   935.9   141.7  924.93   159.8  921.12   170.7  924.47   177.9  924.71
   185.1  922.51   192.3  918.23   195.9     917   211.7  914.03   219.3  912.68
   227.1  912.48   234.9  913.44   246.6  921.42   250.4  922.09   266.2  922.76
   313.6  922.57   325.5  926.14   333.4  927.02   376.8  927.15   392.6   926.2
   400.5   927.1   412.3  931.21   424.2   932.3     436  935.56     440  937.15
   455.7  950.34   479.4   967.4   495.2  980.55     511   991.6   538.6 1014.69
#Mann= 3 , 0 , 0
       0      .1       0   211.7    .045       0   234.9     .06       0
Bank Sta=211.7,234.9
XS Rating Curve= 0 ,0
Exp/Cntr=0.3,0.1

Type RM Length L Ch R = 1 ,21880   ,133,135.1,137.5
XS GIS Cut Line= 6
     1779187.712      350253.522     1779267.573      350199.702
     1779307.504      350187.549     1779361.323      350166.716
     1779415.143      350158.035     1779703.337      350158.035
#Sta/Elev= 30
       0   945.9    19.3  945.93    38.5  944.18    65.5  935.08      77  928.66
    80.9  927.46   107.7  928.88   145.3  926.22   156.2  923.81   170.7  918.33
   181.5  918.74   199.8  917.59   221.5  912.86     231  912.13   238.8  912.38
   242.7  913.68   254.4   922.9   258.4  923.76   301.8  923.07   325.5  926.53
   337.3     927   372.8  927.04   388.6  924.81   420.2  931.64   428.1     935
   443.9  943.61   455.7  947.77     515  989.36   526.8  996.48   538.6  1004.9
#Mann= 3 , 0 , 0
       0     .08       0   221.5    .045       0   242.7     .06       0
Bank Sta=221.5,242.7
XS Rating Curve= 0 ,0
Exp/Cntr=0.3,0.1

Type RM Length L Ch R = 1 ,21744.9 ,175.6,196.6,216.9
XS GIS Cut Line= 2
     1779255.421      350302.133     1779673.823      350281.299
#Sta/Elev= 30
       0  936.32      16  928.46      20  927.45    39.9  927.76    55.9  930.15
    67.8  930.65    71.8   929.4    91.8  916.94   103.7  915.35   115.7  912.69
   127.7  911.71   139.6  911.92   143.6  912.65   147.6  914.85   155.6  921.07
   159.6  922.91   163.6  923.73   187.5  924.59   203.5  926.48   251.4  926.42
   263.3  924.72   271.3  926.58   287.3  933.05   335.1  955.43   359.1   968.2
     375  973.68     383  981.42     391  987.76     407   996.9   418.9 1007.08
#Mann= 3 , 0 , 0
       0     .07       0   115.7    .045       0   143.6     .06       0
Bank Sta=115.7,143.6
XS Rating Curve= 0 ,0
Exp/Cntr=0.3,0.1