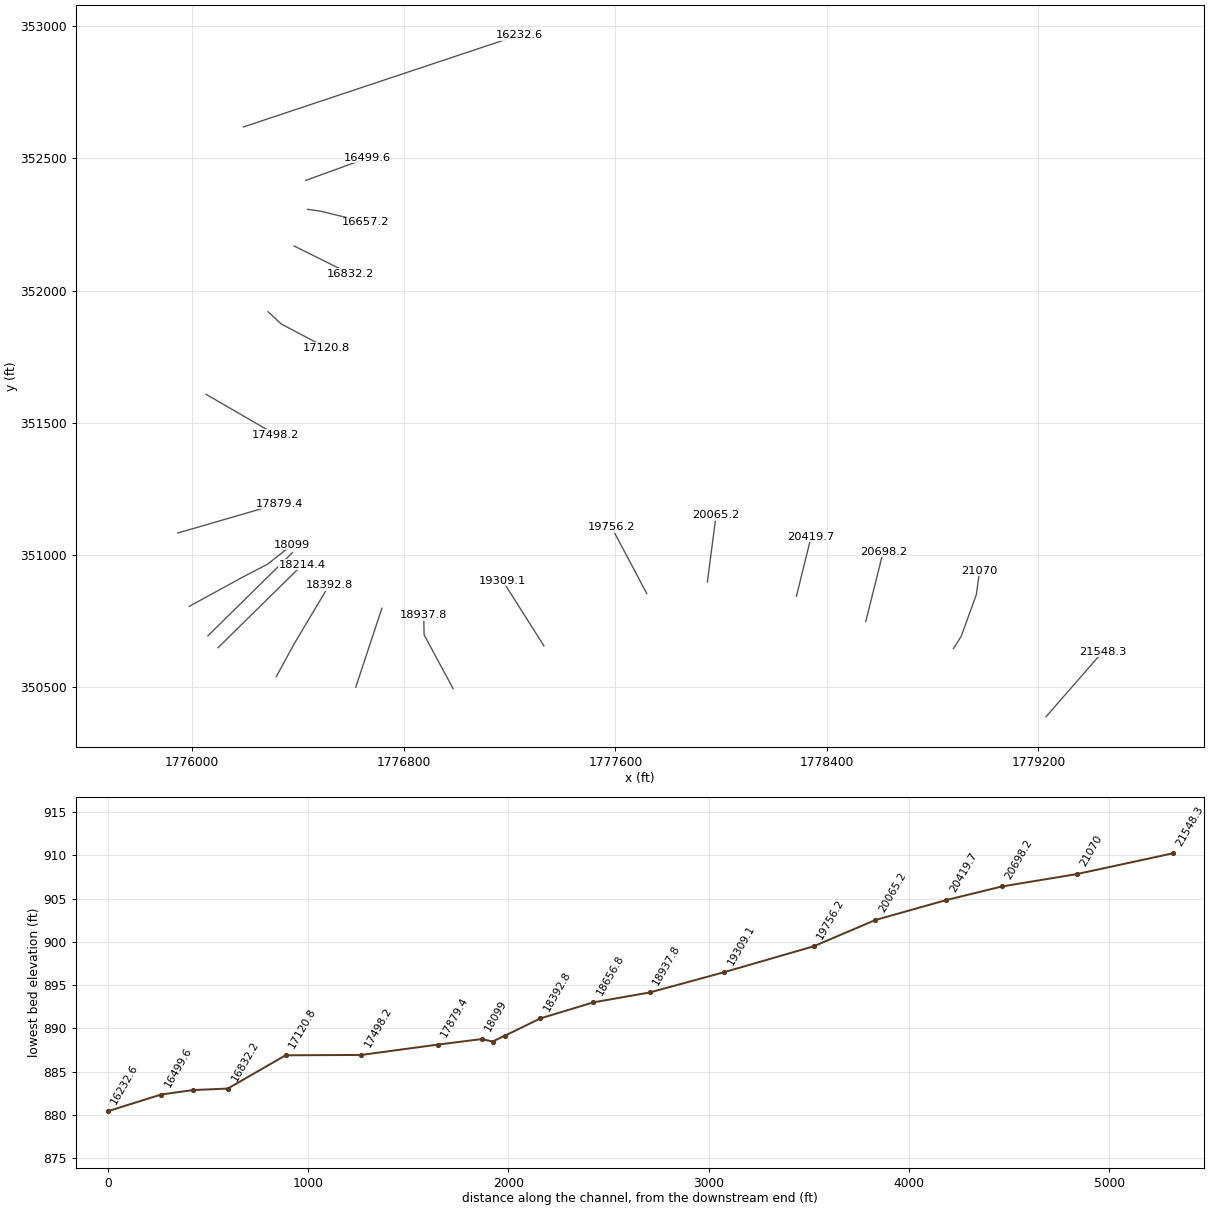
HEC-RAS study WESTFK.prj: WESTFK

--- WESTFK.g01 (geometry) --- (continued)

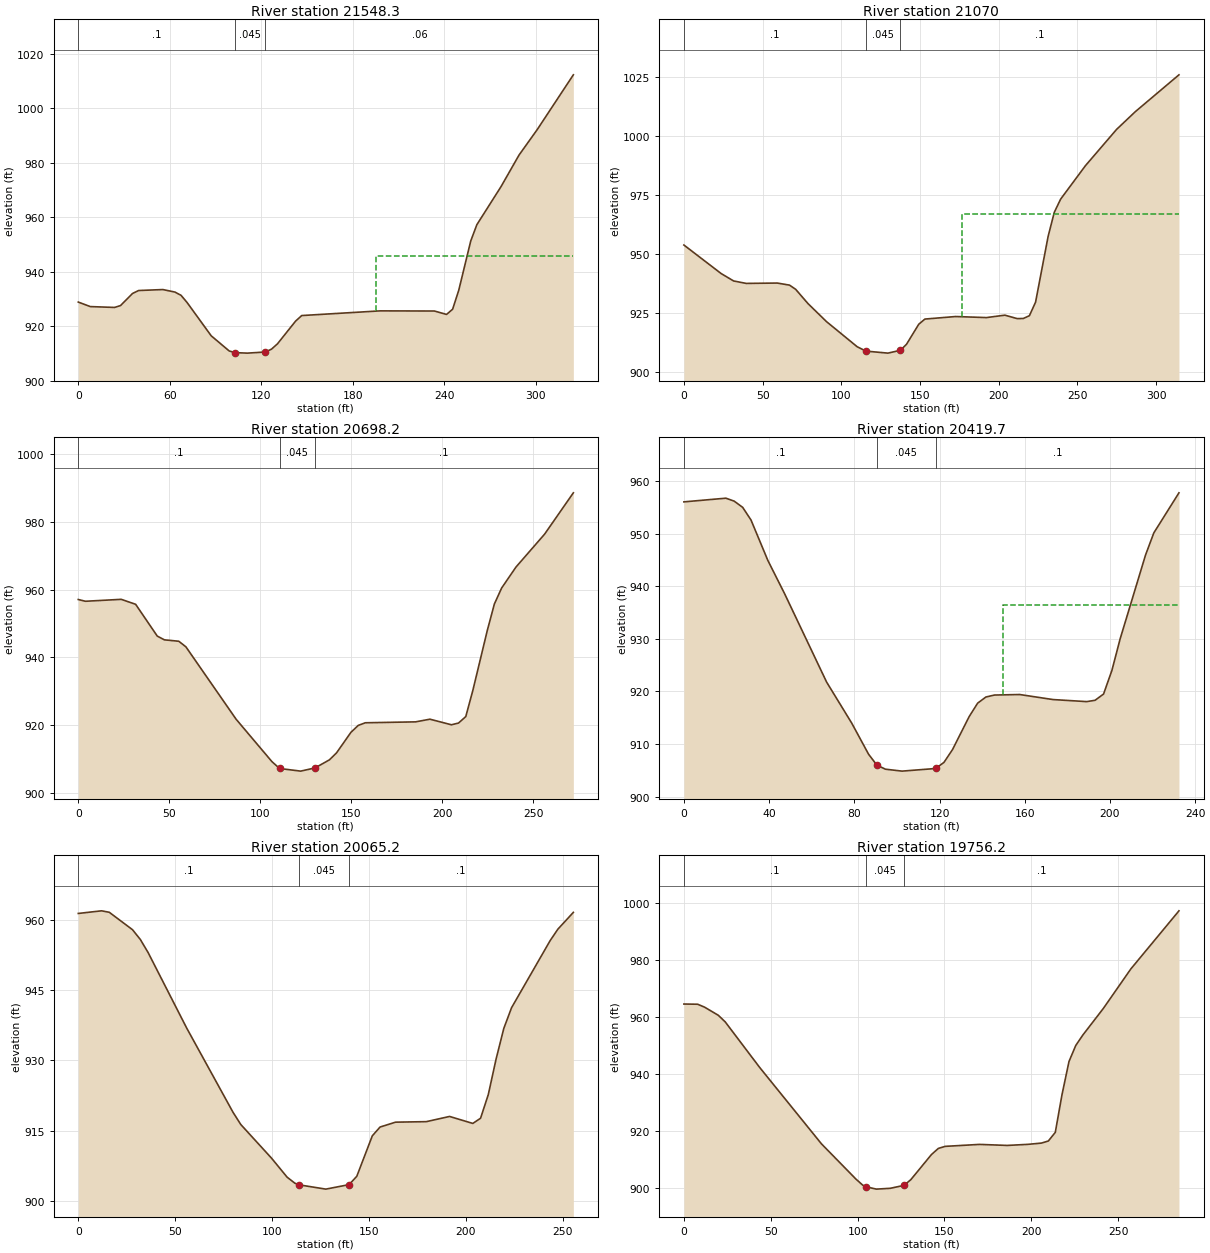
Type RM Length L Ch R = 1 ,21548.3 ,470,478.3,486.4
XS GIS Cut Line= 2
     1779229.379      350388.938     1779442.921       350633.73
#Sta/Elev= 30
       0  928.94     7.9  927.29    23.8  926.98    27.7  927.66    35.6  932.11
    39.6  933.19    55.5  933.54    63.4  932.62    67.4  931.43    71.3  928.85
    87.2  916.57      99  911.01   102.8  910.39   110.9  910.21   122.8  910.62
   126.8  911.68   130.7  913.64   142.6  921.98   146.6     924   198.1  925.72
   233.7  925.66   241.6  924.41   245.6  926.33   249.6  933.24   257.5   951.4
   261.5  957.35   277.3  971.27   289.2  982.93   301.1  992.25   324.8 1012.35
#Mann= 3 , 0 , 0
       0      .1       0   102.8    .045       0   122.8     .06       0
#XS Ineff= 2 , 0
                          195.62          945.77
Permanent Ineff=
       F       F
Bank Sta=102.8,122.8
XS Rating Curve= 0 ,0
Exp/Cntr=0.3,0.1

Type RM Length L Ch R = 1 ,21070   ,369.1,371.8,373.8
XS GIS Cut Line= 4
     1778878.684      350645.883     1778908.198      350692.758
      1778965.49      350850.744     1778977.643      350941.022
#Sta/Elev= 30
       0  953.75    23.7  941.61    31.6  938.48    39.6  937.44    59.3  937.59
    67.1  936.71      71  934.93    78.8  928.89    90.6   921.2   110.1  910.52
   115.6  908.68   129.6  907.82   137.5  909.02   141.4  911.56   149.2  920.09
   153.1  922.29   172.6  923.37   192.2  922.92   203.9  923.95   211.7  922.49
   215.6  922.53   219.5  923.73   223.4  929.47   231.4  957.47   235.3  967.63
   239.3  973.22   255.1  987.47   274.9 1002.89   286.8 1010.42   314.5 1026.06
#Mann= 3 , 0 , 0
       0      .1       0   115.6    .045       0   137.5      .1       0
#XS Ineff= 2 , 0
                           176.4          966.96
Permanent Ineff=
       F       F
Bank Sta=115.6,137.5
XS Rating Curve= 0 ,0
Exp/Cntr=0.3,0.1

Type RM Length L Ch R = 1 ,20698.2 ,278.3,278.5,278.4
XS GIS Cut Line= 2
     1778547.087      350748.313     1778613.059      351012.202
#Sta/Elev= 30
       0  957.09     3.9  956.57    23.6  957.14    31.5  955.68    43.4  946.28
    47.3  945.18    55.2  944.76    59.1  943.13    86.7  921.74   106.4   909.2
   110.6  907.18   122.2   906.4   130.1  907.35     138  909.74   141.9   911.8
   149.8  917.86   153.8   919.9   157.7  920.68   185.3  920.95   193.2  921.74
     205  920.09   208.9   920.6   212.9  922.51   216.8  930.28   224.7   947.9
   228.6  955.75   232.6  960.48   240.5  966.69   256.2  976.39     272   988.6
#Mann= 3 , 0 , 0
       0      .1       0   110.6    .045       0   130.1      .1       0
Bank Sta=110.6,130.1
XS Rating Curve= 0 ,0
Exp/Cntr=0.3,0.1

Type RM Length L Ch R = 1 ,20419.7 ,351.6,354.5,356.7
XS GIS Cut Line= 2
     1778284.934      350843.799      1778340.49      351069.494
#Sta/Elev= 30
       0  956.04    19.7  956.74    23.6  956.18    27.6  954.99    31.5  952.59
    39.4  944.91    47.3  938.55      67  921.76    78.8  913.95    86.7  908.04
    90.6  905.97    94.6   905.2   102.4  904.83   118.2  905.33   122.1   906.5
   126.1  908.93   133.9  915.19   137.9  917.76   141.8  918.93   145.8   919.3
   157.6   919.4   173.3  918.44   189.1  918.05     193   918.3     197  919.49
   200.9  923.96   204.8     930   216.7  945.92   220.6  950.14   232.4  957.76
#Mann= 3 , 0 , 0
       0      .1       0    90.6    .045       0   118.2      .1       0
#XS Ineff= 2 , 0
                          149.69          936.35
Permanent Ineff=
       F       F
Bank Sta=90.6,118.2
XS Rating Curve= 0 ,0
Exp/Cntr=0.3,0.1

Type RM Length L Ch R = 1 ,20065.2 ,294.8,309,322.8
XS GIS Cut Line= 2
     1777948.129      350897.619     1777981.115      351151.091
#Sta/Elev= 30
       0  961.31      12  961.87      16  961.56      28  957.84      32  955.78
      36  953.01    55.9  936.92    79.9   918.9    83.9   916.3    99.8  909.11
   107.8  905.08   111.8  903.79   114.2  903.42   127.8  902.52   139.8  903.48
   143.8  905.26   151.8  913.88   155.8  915.76   163.8   916.8   179.7  916.91
   191.7  918.02   203.7  916.53   207.7  917.64   211.7   922.7   215.7  930.24
   219.7   936.8   223.7  941.21   243.6   955.5   247.6  957.95   255.6  961.54
#Mann= 3 , 0 , 0
       0      .1       0   114.2    .045       0   139.8      .1       0
Bank Sta=114.2,139.8
XS Rating Curve= 0 ,0
Exp/Cntr=0.3,0.1

Type RM Length L Ch R = 1 ,19756.2 ,445.3,447.1,448.8
XS GIS Cut Line= 2
     1777718.962      350854.216     1777585.282      351105.952
#Sta/Elev= 30
       0  964.46     7.9  964.39    11.9  963.36    19.8  960.51    23.8  958.18
    43.6  942.21    79.2  915.37      99  903.03   102.9   900.9   105.1  900.28
   110.8  899.48   118.8  899.77   126.7   900.8   130.6  902.78   142.5  911.61
   146.5  913.78   150.4  914.49   170.2  915.18   186.1  914.82   197.9  915.19
   205.8  915.64   209.8  916.37   213.8   919.4   217.7  932.74   221.7   944.3
   225.6  949.92   229.6  953.52   241.5  962.94   257.3  976.78     285  997.18
#Mann= 3 , 0 , 0
       0      .1       0   105.1    .045       0   126.7      .1       0
Bank Sta=105.1,126.7
XS Rating Curve= 0 ,0
Exp/Cntr=0.3,0.1

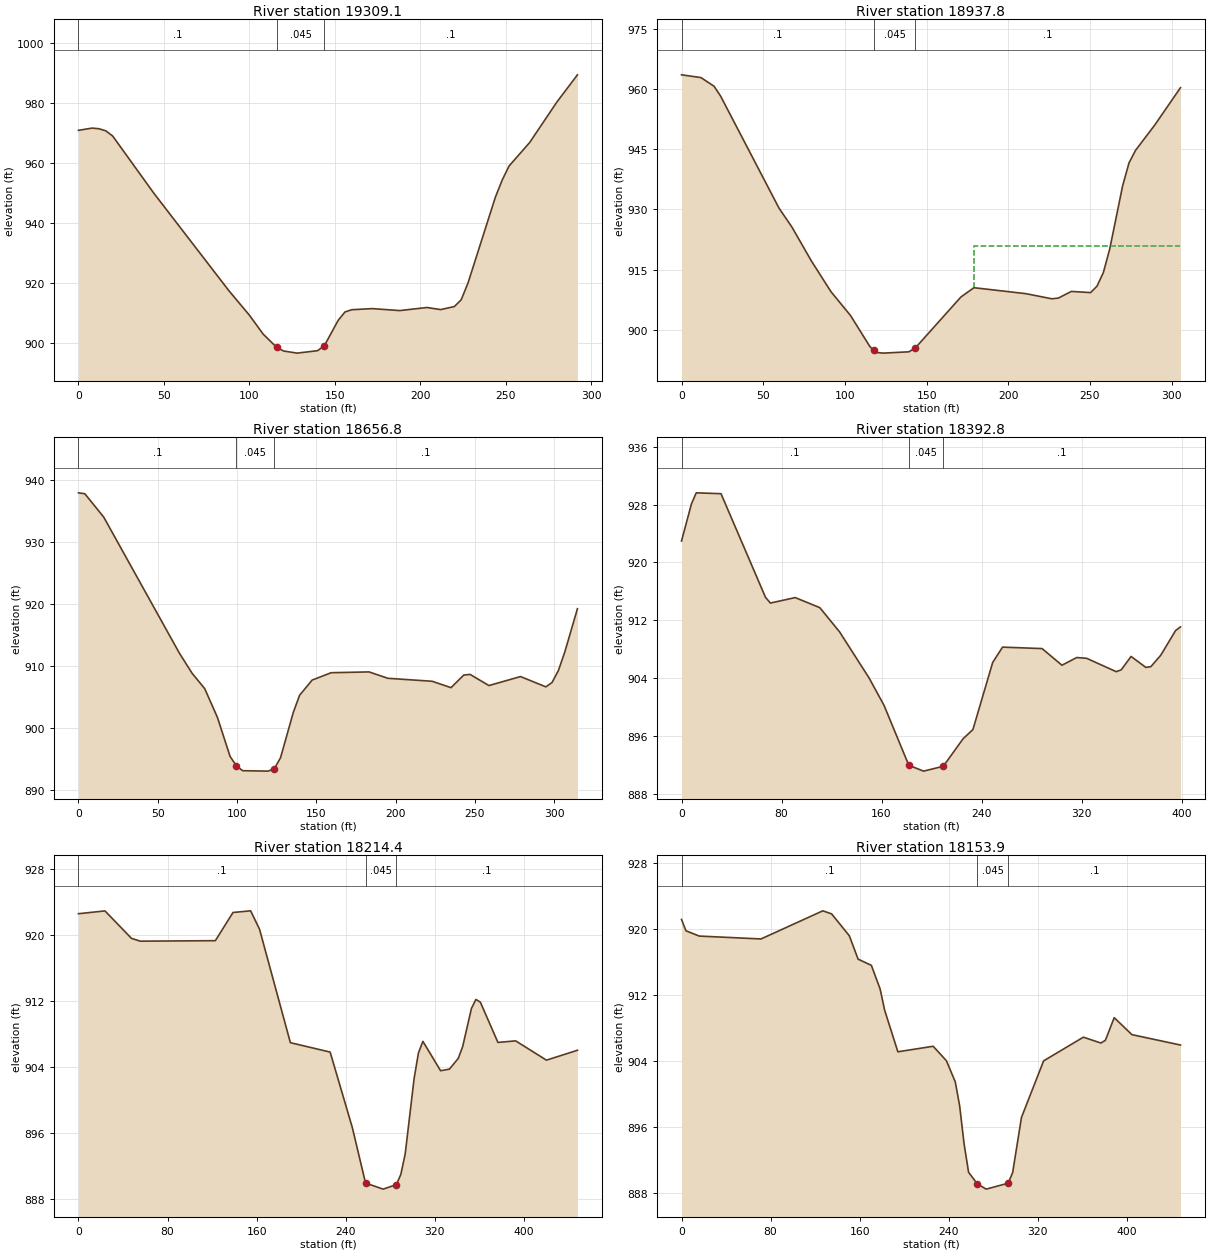
Type RM Length L Ch R = 1 ,19309.1 ,372.8,371.4,369.8
XS GIS Cut Line= 2
     1777330.073      350656.299     1777173.823      350902.827
#Sta/Elev= 30
       0  970.91       8  971.66      12  971.44      16  970.74      20  969.01
      44  949.97      88  917.34     100  909.15     108  902.87     116  898.39
     120   897.2   127.9  896.49   139.9  897.31   143.9  899.02   151.9  907.42
   155.9  910.24   159.9  910.99   171.9  911.36   187.9   910.7   203.9  911.73
   211.9  911.03   219.9  912.05   223.9  914.32   227.9  919.95   243.9  948.59
   247.9  954.33   251.9  958.99   263.9   966.8   279.9  980.38   291.9  989.45
#Mann= 3 , 0 , 0
       0      .1       0     116    .045       0   143.9      .1       0
Bank Sta=116,143.9
XS Rating Curve= 0 ,0
Exp/Cntr=0.3,0.1

Type RM Length L Ch R = 1 ,18937.8 ,298.9,280.9,262
XS GIS Cut Line= 3
     1776986.323      350494.841     1776876.948      350697.966
     1776875.212      350772.619
#Sta/Elev= 30
       0  963.57    11.9  962.88    19.9  960.73    23.9  958.28    59.7   930.3
    67.6  925.58    79.6  917.07    91.5  909.47   103.4  903.56   115.4  895.73
   117.6  894.93   119.3  894.32   123.3  894.15   139.2  894.48   143.2  895.48
     171  908.15     179  910.47   210.8  908.98   226.7   907.7   230.7  907.89
   238.6  909.54   250.4  909.25   254.3  910.85   258.2  914.24   262.1  920.12
     270  935.88   273.9  941.59   277.9  944.73   289.6  951.01   305.4  960.36
#Mann= 3 , 0 , 0
       0      .1       0   117.6    .045       0   143.2      .1       0
#XS Ineff= 2 , 0
                          179.19          920.82
Permanent Ineff=
       F       F
Bank Sta=117.6,143.2
XS Rating Curve= 0 ,0
Exp/Cntr=0.3,0.1

Type RM Length L Ch R = 1 ,18656.8 ,268.8,264.1,258.9
XS GIS Cut Line= 2
     1776618.268      350500.049     1776717.226       350798.66
#Sta/Elev= 30
       0  937.89       4  937.74    15.9  933.98    63.7     912    71.7  908.77
    79.6  906.31    87.6  901.68    95.6  895.37    99.6  893.86   103.5  893.08
   119.5  893.01   123.4  893.36   127.4  895.17   135.4  902.44   139.4  905.24
   147.3  907.69   159.3  908.88   183.2  909.01   195.1  907.98     223   907.5
   234.9  906.47   242.9   908.5   246.9  908.61   258.8  906.81   278.7  908.26
   294.7   906.6   298.6  907.31   302.6  909.23   306.6   912.2   314.6   919.2
#Mann= 3 , 0 , 0
       0      .1       0    99.6    .045       0   123.4      .1       0
Bank Sta=99.6,123.4
XS Rating Curve= 0 ,0
Exp/Cntr=0.3,0.1

Type RM Length L Ch R = 1 ,18392.8 ,184.1,178.4,172.5
XS GIS Cut Line= 3
     1776317.921       350539.98     1776383.893      350661.508
     1776517.573      350885.466
#Sta/Elev= 30
       0  922.97     7.9  928.08    11.8  929.63    31.6  929.51    67.2  915.18
    71.1  914.39    90.9  915.15   110.6  913.76   126.4  910.42   150.1  904.02
     162  900.25   181.8  891.97   193.6  891.16   209.4  891.83   225.2  895.63
   233.1  896.91   248.9  906.18   256.8   908.3   288.4   908.1   304.3   905.8
   316.1  906.86     324  906.76   347.7  904.91   351.7  905.16   359.6  907.01
   371.4   905.5   375.4   905.6   383.3  907.17   395.2  910.59   399.1   911.1
#Mann= 3 , 0 , 0
       0      .1       0   181.8    .045       0   209.4      .1       0
Bank Sta=181.8,209.4
XS Rating Curve= 0 ,0
Exp/Cntr=0.3,0.1

Type RM Length L Ch R = 1 ,18214.4 ,60.1,60.5,60.9
XS GIS Cut Line= 2
     1776097.434      350649.355     1776416.879      350963.591
#Sta/Elev= 30
       0  922.55    23.8  922.89    47.6  919.56    55.5  919.22   122.9  919.28
   138.8   922.7   154.6   922.9   162.6  920.67   190.3  906.91     226  905.77
   245.9  896.63   257.8  889.89   273.6  889.15   285.5   889.7   289.5  890.94
   293.4  893.41   301.4  902.54   305.3  905.66   309.3  907.07   325.2  903.51
   333.1   903.7     341  904.99     345  906.42   352.9  911.06   356.9  912.15
   360.9  911.83   376.7  906.94   392.6  907.13   420.3  904.79   448.1  905.99
#Mann= 3 , 0 , 0
       0      .1       0   257.8    .045       0   285.5      .1       0
Bank Sta=257.8,285.5
XS Rating Curve= 0 ,0
Exp/Cntr=0.3,0.1

Type RM Length L Ch R = 1 ,18153.9 ,61.6,54.9,47.3
XS GIS Cut Line= 2
      1776059.24      350694.494     1776378.684       351008.73
#Sta/Elev= 30
       0  921.18       4  919.81    15.9  919.17    71.4  918.82   126.9  922.23
   134.8  921.86   150.7  919.21   158.6  916.37   170.5  915.62   178.4  912.74
   182.4   910.2   194.3  905.14     226  905.81   237.9  904.06   245.9  901.48
   249.8  898.58   253.8  893.96   257.8  890.54   265.7  889.12   273.6  888.49
   293.4  889.21   297.4   890.5   305.3  897.18   325.2  904.04   360.9  906.91
   376.7   906.2   380.7  906.54   388.6  909.28   404.5  907.22   448.1  905.96
#Mann= 3 , 0 , 0
       0      .1       0   265.7    .045       0   293.4      .1       0
Bank Sta=265.7,293.4
XS Rating Curve= 0 ,0
Exp/Cntr=0.3,0.1

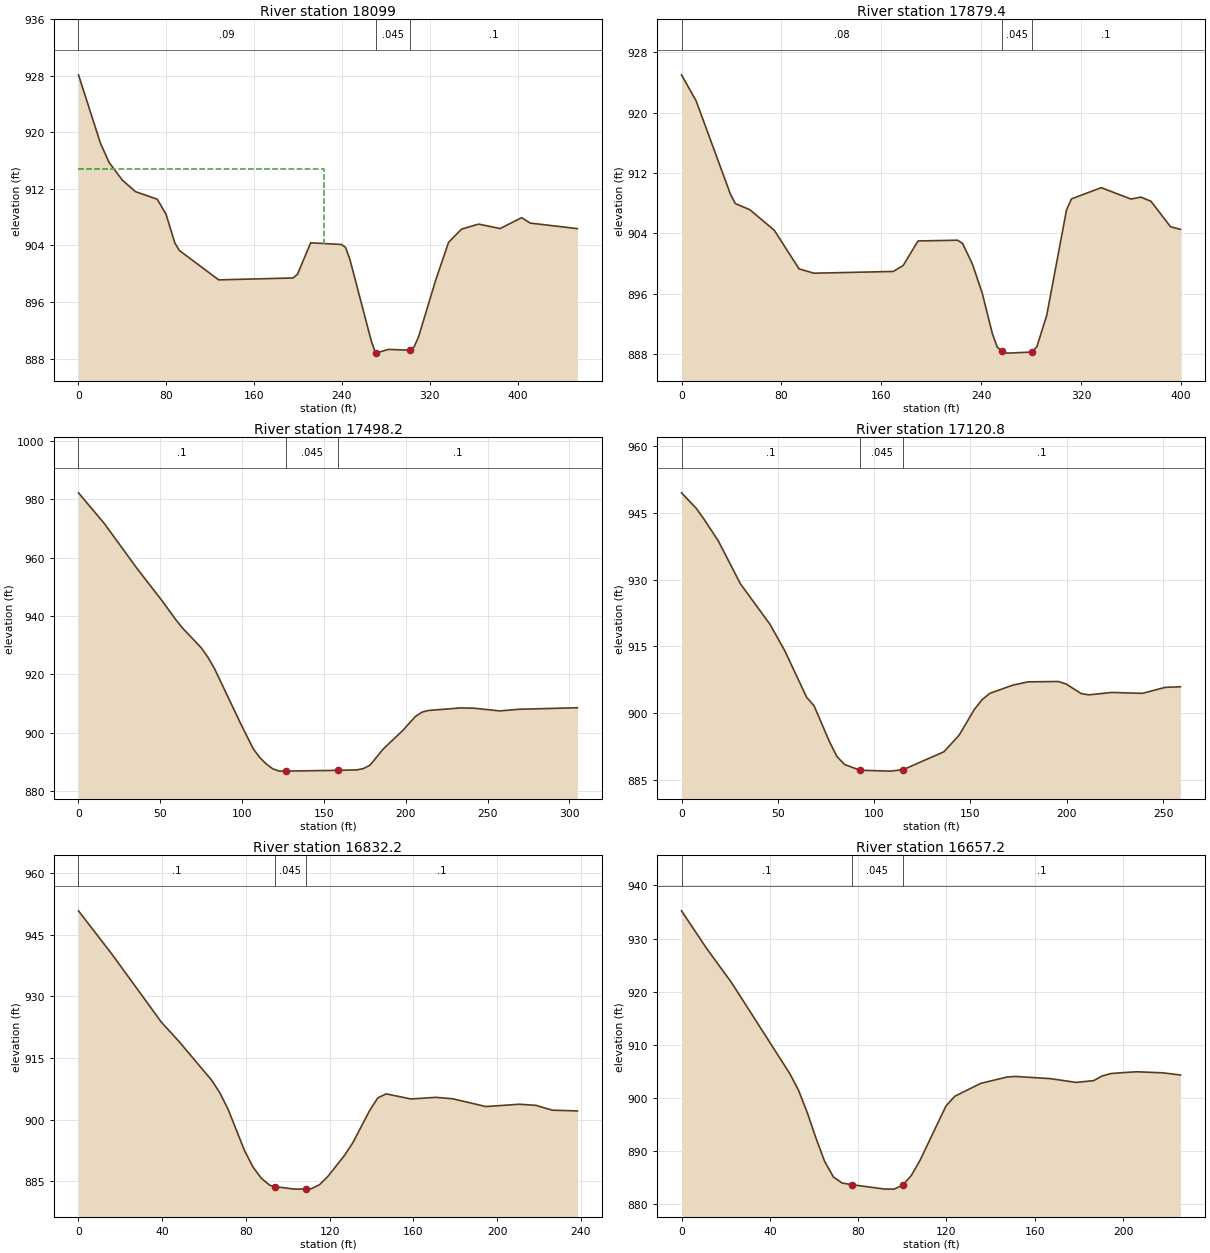
Type RM Length L Ch R = 1 ,18099   ,223.8,219.6,215.1
XS GIS Cut Line= 4
     1775988.059      350805.605     1776194.657      350918.452
     1776284.934      350965.327     1776376.948      351038.244
#Sta/Elev= 30
       0  928.13      20  918.46    27.9  915.73    39.9  913.25    51.9  911.61
    71.8  910.53    79.8  908.39    87.8  904.34    91.8   903.3   127.7  899.13
   195.5   899.4   199.5  899.93   211.5  904.37   239.3  904.14   243.2  903.74
   247.2  902.04   266.7   890.5   270.6  888.77   282.4   889.3   301.9  889.18
   305.8  889.69   309.7  891.04   325.4   899.1   337.1  904.43   348.9   906.3
   364.5  907.02   384.1  906.39   403.7  907.93   411.5  907.16   454.5  906.38
#Mann= 3 , 0 , 0
       0     .09       0   270.6    .045       0   301.9      .1       0
#XS Ineff= 2 , 0
          223.65  914.76
Permanent Ineff=
       F       F
Bank Sta=270.6,301.9
XS Rating Curve= 0 ,0
Exp/Cntr=0.3,0.1

Type RM Length L Ch R = 1 ,17879.4 ,399.2,381.3,362.2
XS GIS Cut Line= 3
     1775944.657      351083.383     1776012.365       351102.48
     1776328.337      351194.494
#Sta/Elev= 30
       0     925    11.7  921.55    39.1  909.22      43  907.95    54.7  907.13
    74.3   904.4    94.1  899.29     106  898.72   169.5  898.95   177.4  899.73
   189.3  902.99     221  903.09     225  902.66   232.9  899.91   240.8  896.03
   248.8  890.73   252.7  888.94   256.6  888.37   260.7  888.13   280.5  888.27
   284.5     889   292.4  893.18   308.2  907.11   312.2  908.57     336  910.05
   359.8  908.54   367.7   908.8   375.7  908.26   391.5  904.87   399.4  904.53
#Mann= 3 , 0 , 0
       0     .08       0   256.6    .045       0   280.5      .1       0
Bank Sta=256.6,280.5
XS Rating Curve= 0 ,0
Exp/Cntr=0.3,0.1

Type RM Length L Ch R = 1 ,17498.2 ,376.2,377.4,378.5
XS GIS Cut Line= 2
     1776052.296      351607.688     1776316.184       351454.91
#Sta/Elev= 30
       0  982.13    15.8  971.63    35.6  956.38    51.5   944.9    59.4  938.79
    63.4  935.98    75.2  929.02    79.2  925.78    83.2  921.92      99  903.31
   106.9  894.47   110.9  891.53   114.8  889.37   118.8   887.7   122.8  886.94
   126.7  886.95   158.4  887.21   170.3  887.37   174.2  887.83   178.2  889.01
   186.1  894.43     198  900.76   205.9  905.63   209.9  907.11   213.8  907.68
   233.6  908.56   241.6  908.47   257.4  907.54   269.3   908.1   304.9  908.62
#Mann= 3 , 0 , 0
       0      .1       0   126.7    .045       0   158.4      .1       0
Bank Sta=126.7,158.4
XS Rating Curve= 0 ,0
Exp/Cntr=0.3,0.1

Type RM Length L Ch R = 1 ,17120.8 ,288.1,288.6,289.2
XS GIS Cut Line= 3
     1776286.671      351920.188     1776337.018      351873.313
     1776505.421      351784.772
#Sta/Elev= 30
       0   949.5     7.6  946.03    11.5  943.69    19.1  938.69    30.6  929.02
    45.9  919.95    53.5  914.06      65  903.47    68.8   901.6    76.7  893.63
    80.7  890.18    84.6  888.41    92.6   887.1   108.4   886.9   115.1  887.24
   136.2  891.25   144.1  894.98     152  900.77     156  902.96     160  904.38
   171.8  906.22   179.8  906.98   195.6  907.06   199.6  906.51   207.5  904.33
   211.5  904.06   223.4   904.6   239.2  904.39   251.1  905.74     259  905.88
#Mann= 3 , 0 , 0
       0      .1       0    92.6    .045       0   115.1      .1       0
Bank Sta=92.6,115.1
XS Rating Curve= 0 ,0
Exp/Cntr=0.3,0.1

Type RM Length L Ch R = 1 ,16832.2 ,169.8,175,179.8
XS GIS Cut Line= 2
     1776385.629      352168.452     1776599.171      352062.549
#Sta/Elev= 30
       0  950.85    15.9  940.35    39.7  923.66    47.7  919.22    63.6  909.61
    67.5  906.56    71.5  902.49    79.4  892.38    83.4  888.43    87.4   885.7
    91.4     884    93.7  883.68   103.3  883.06   108.7  883.09   111.2  883.15
   115.2  884.15   119.2  886.18   127.1  891.28   131.1  894.38     139  902.09
     143  905.29     147  906.26   158.9  905.02   170.8  905.42   178.8  905.07
   194.7  903.17   210.6  903.74   218.5  903.47   226.4  902.29   238.4  902.11
#Mann= 3 , 0 , 0
       0      .1       0    93.7    .045       0   108.7      .1       0
Bank Sta=93.7,108.7
XS Rating Curve= 0 ,0
Exp/Cntr=0.3,0.1

Type RM Length L Ch R = 1 ,16657.2 ,144.2,157.6,171
XS GIS Cut Line= 3
     1776435.976      352307.341     1776484.587      352300.397
     1776656.462       352258.73
#Sta/Elev= 30
       0  935.22    11.3  928.19    22.7   921.7    49.1  904.57      53  901.48
      57  897.22    60.9  892.48    64.8  888.12    68.8  885.17    72.7  884.04
      77  883.72    92.3  882.88    96.3  882.89   100.2  883.63   104.1  885.45
   108.1  888.35   119.8  898.53   123.8  900.35   135.6  902.78   147.4  903.96
   151.3  904.07     167  903.66   178.8  902.95   186.7  903.29   190.6  904.17
   194.5  904.62   202.4  904.86   206.3  904.95   218.1  904.75     226  904.34
#Mann= 3 , 0 , 0
       0      .1       0      77    .045       0   100.2      .1       0
Bank Sta=77,100.2
XS Rating Curve= 0 ,0
Exp/Cntr=0.3,0.1

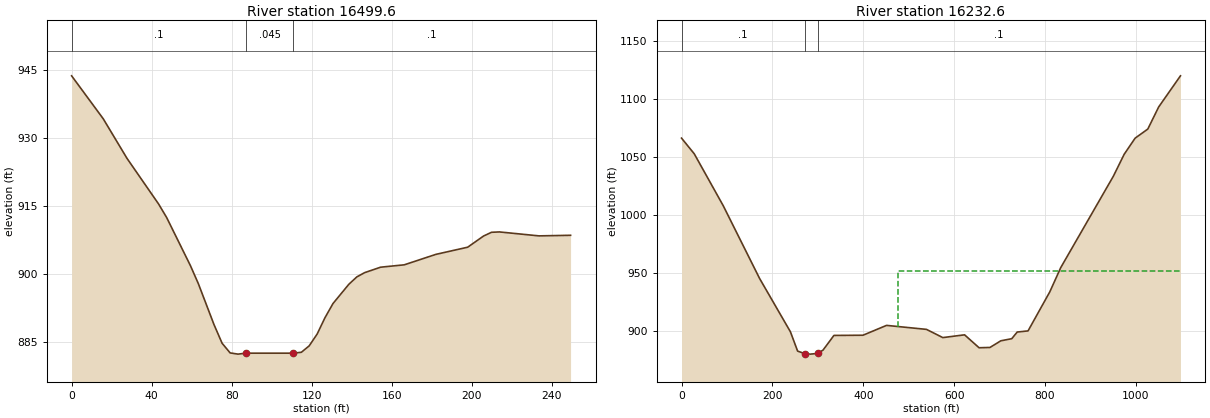
Type RM Length L Ch R = 1 ,16499.6 ,267.7,266.9,266.1
XS GIS Cut Line= 2
     1776429.032      352416.716     1776663.407      352501.785
#Sta/Elev= 30
       0  943.61    15.8  934.16    27.7  925.43    43.5  915.38    47.5  912.42
    59.4  901.81    63.3   897.9    71.2  888.81    75.2  884.76    79.2  882.64
    83.1  882.37    87.1  882.58   110.8  882.58   114.8  882.78   118.7  884.19
   122.7   886.8   126.6  890.39   130.6   893.5   138.5  897.73   142.5  899.36
   146.4   900.3   154.4   901.5   166.2  902.02     182  904.32   197.9   905.9
   205.8  908.35   209.8  909.18   213.7  909.26   233.5  908.39   249.3  908.52
#Mann= 3 , 0 , 0
       0      .1       0    87.1    .045       0   110.8      .1       0
Bank Sta=87.1,110.8
XS Rating Curve= 0 ,0
Exp/Cntr=0.3,0.1

Type RM Length L Ch R = 1 ,16232.6 ,426.9,439.3,451
XS GIS Cut Line= 2
     1776193.664      352618.956     1777235.331      352966.178
#Sta/Elev= 30
       0 1066.59      28 1053.09    91.8 1008.35   171.7  945.72   239.6  899.74
   255.5  883.05   271.5  880.82   283.5  880.44   299.5  881.03   311.4   883.9
   335.4  896.55   399.3  896.72   451.2  905.21     539  901.77     575  894.69
   622.9  897.07   654.8  885.93   678.8  886.19   702.7  891.93   726.7  893.73
   738.7  899.47   762.6  900.46   810.5  934.15   834.5  954.97   950.3 1033.74
   974.2 1052.71   998.2 1066.55  1026.1 1074.38  1050.1 1093.46    1098 1120.27
#Mann= 3 , 0 , 0
       0      .1       0   271.5    .045       0   299.5      .1       0
#XS Ineff= 2 , 0
                          477.24          952.17
Permanent Ineff=
       F       F
Bank Sta=271.5,299.5
XS Rating Curve= 0 ,0
Exp/Cntr=0.3,0.1