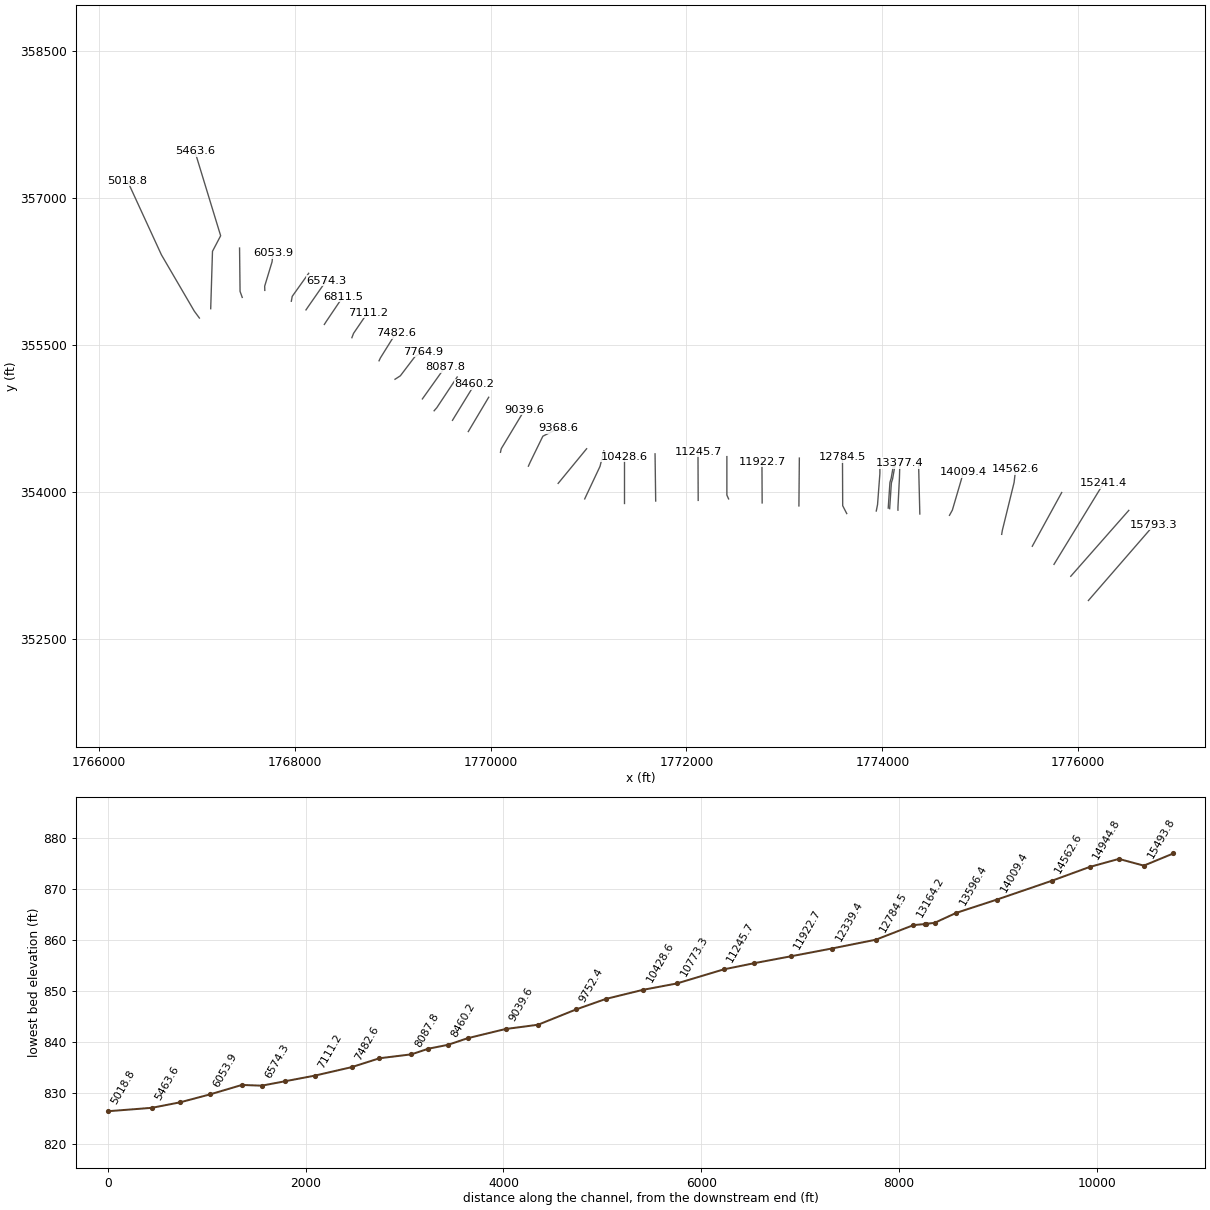
HEC-RAS study WESTFK.prj: WESTFK

--- WESTFK.g01 (geometry) --- (continued)

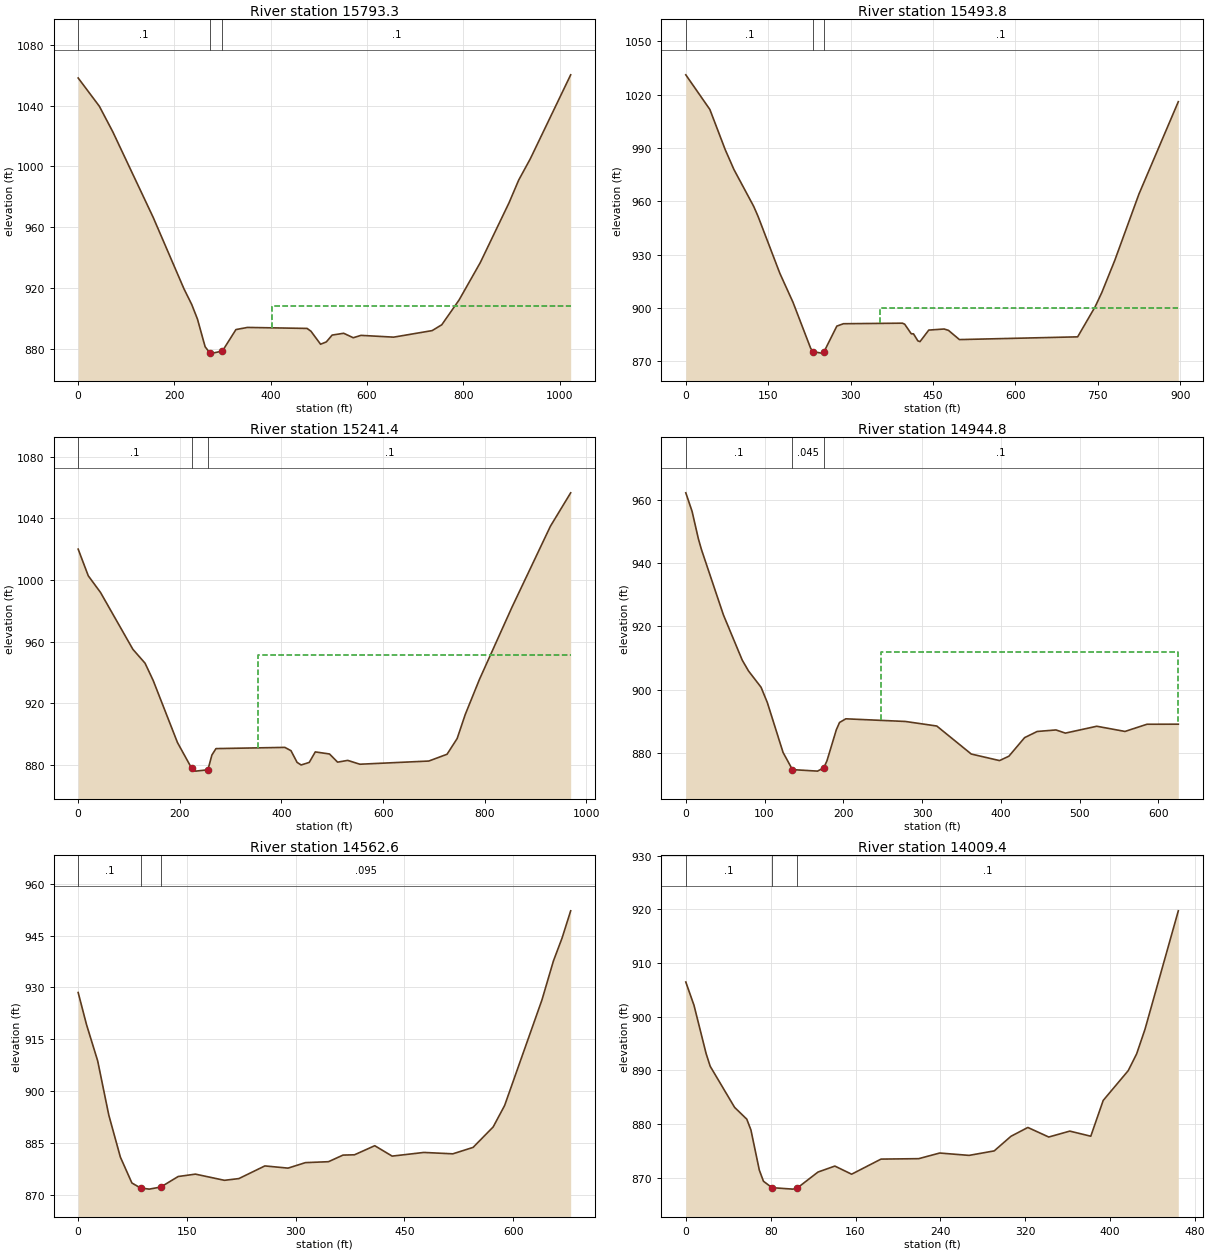
Type RM Length L Ch R = 1 ,15793.3 ,299.7,299.5,299.4
XS GIS Cut Line= 2
     1776104.688      352892.393     1776775.261      353664.963
#Sta/Elev= 30
       0 1058.22      44 1039.61    71.9 1022.79   155.8  966.41   219.8   919.3
   235.8  909.06   247.8  899.39   263.7  881.17   272.9  877.35   279.7  876.96
   299.7  878.38   327.7  892.48   351.7  893.89   475.5  893.23   483.5   891.4
   503.5  882.82   515.5  884.36   527.5  888.84   551.5  890.04   571.4   887.1
   587.4  888.66   655.4  887.49   735.3   891.8   755.3  895.66   791.2  911.97
   835.2  936.57   895.1   976.1   915.1  991.01   939.1 1004.96    1023  1060.3
#Mann= 3 , 0 , 0
       0      .1       0   272.9    .045       0   299.7      .1       0
#XS Ineff= 2 , 0
                          402.83          908.04
Permanent Ineff=
       F       F
Bank Sta=272.9,299.7
XS Rating Curve= 0 ,0
Exp/Cntr=0.3,0.1

Type RM Length L Ch R = 1 ,15493.8 ,248.5,252.4,256.3
XS GIS Cut Line= 2
     1775924.567      353139.789     1776517.015      353812.532
#Sta/Elev= 30
       0 1031.14    43.8 1011.65    71.7  989.08    87.6  977.88   123.5  957.18
   131.5  951.53   171.3  919.37   195.2  903.11   227.1  877.41   231.1  875.42
     247  874.56     251  874.97   274.9  889.76   286.9   891.1   394.4  891.41
   398.4  890.83   410.4  885.43   414.4  885.43   422.3  881.49   426.3  881.03
   442.2  887.52   470.1  888.13   478.1  887.37     498  882.18   713.2  883.72
     745  900.64     757  908.54   780.9  926.86   824.7  964.02   896.4 1016.03
#Mann= 3 , 0 , 0
       0      .1       0   231.1    .045       0     251      .1       0
#XS Ineff= 2 , 0
                          353.41          900.18
Permanent Ineff=
       F       F
Bank Sta=231.1,251
XS Rating Curve= 0 ,0
Exp/Cntr=0.3,0.1

Type RM Length L Ch R = 1 ,15241.4 ,295.5,296.6,297.6
XS GIS Cut Line= 2
     1775753.126      353261.317     1776258.768       354088.14
#Sta/Elev= 30
       0 1020.07    19.9 1002.75    43.9  991.97   107.7  954.99   131.6     946
   147.6  934.79   195.4  894.46   223.4   877.7   231.3  875.88   255.3  876.75
   263.2  886.37   271.2  890.51   406.8   891.3   418.8  889.15   430.8  881.56
   438.7  879.88   454.7  881.53   466.6  888.36   494.6  887.02   510.5  881.72
   530.5  882.85   554.4  880.36     690  882.43   725.9  886.84   745.8  897.06
   761.8  912.73   789.7  935.48   853.5  982.22   929.3 1034.94   969.2 1056.64
#Mann= 3 , 0 , 0
       0      .1       0   223.4    .045       0   255.3      .1       0
#XS Ineff= 2 , 0
                          353.41          951.08
Permanent Ineff=
       F       F
Bank Sta=223.4,255.3
XS Rating Curve= 0 ,0
Exp/Cntr=0.3,0.1

Type RM Length L Ch R = 1 ,14944.8 ,375.4,382.2,387.2
XS GIS Cut Line= 2
     1775531.462       353446.23     1775831.809      353994.841
#Sta/Elev= 30
       0  962.22       8  956.35    15.9  947.77    19.9  944.28    47.8  923.63
    71.7  909.34    79.7  905.92    95.6  900.78   103.6  895.91   123.5   880.2
   135.4  874.77   167.3  874.29   175.3  875.36   179.3  877.59   191.2   887.4
   195.2  889.66   203.2  890.82   278.9  889.98   318.7  888.54   362.5  879.69
   398.4  877.62   410.3  879.01   430.2  884.87   446.2  886.82   470.1   887.3
     482   886.3   521.9  888.47   557.7  886.83   585.6   889.1   625.4  889.12
#Mann= 3 , 0 , 0
       0      .1       0   135.4    .045       0   175.3      .1       0
#XS Ineff= 2 , 0
                          247.39          911.89
Permanent Ineff=
       F       F
Bank Sta=135.4,175.3
XS Rating Curve= 0 ,0
Exp/Cntr=0.3,0.1

Type RM Length L Ch R = 1 ,14562.6 ,553.7,553.2,551.5
XS GIS Cut Line= 4
     1775218.962      353567.758     1775225.907      353609.424
     1775345.698      354097.272     1775361.323      354230.952
#Sta/Elev= 30
       0   928.5    11.5  919.22    26.9  908.72    42.2  893.05    58.2  880.86
    74.1  873.36    86.1   871.9    98.1  871.58     114  872.19   137.9  875.23
   161.8  875.92   201.7  874.13   221.6  874.63   257.5   878.3   289.4  877.66
   313.4  879.25   345.2  879.52   365.2  881.43   381.1  881.52     409  884.15
     433  881.14   476.8   882.2   516.7   881.8   544.6  883.66   572.3  889.58
   588.1  895.79   639.6  926.37   655.4  937.64   667.3  944.26   679.2  952.15
#Mann= 3 , 0 , 0
       0      .1       0    86.1    .045       0     114    .095       0
Bank Sta=86.1,114
XS Rating Curve= 0 ,0
Exp/Cntr=0.3,0.1

Type RM Length L Ch R = 1 ,14009.4 ,405.2,413,419.5
XS GIS Cut Line= 4
     1774685.976      353762.202      1774715.49      353816.022
     1774805.768      354123.313     1774826.601      354203.174
#Sta/Elev= 30
       0  906.46     7.7  902.14    19.2   893.1      23  890.77      46  883.12
    57.5  880.92    61.4   878.9    69.3  871.44    73.2  869.37    81.2  868.17
   100.9   867.9   104.9  868.08   124.6  871.08   140.5  872.19   156.3  870.68
     184  873.49   219.5  873.57   239.3  874.62     267  874.18   290.7  875.02
   306.5  877.74   322.4  879.38   342.1   877.6   361.9   878.7   381.7  877.75
   393.4  884.41     417  889.96   424.9  893.07   432.8  897.66   464.2  919.71
#Mann= 3 , 0 , 0
       0      .1       0    81.2    .045       0   104.9      .1       0
Bank Sta=81.2,104.9
XS Rating Curve= 0 ,0
Exp/Cntr=0.3,0.1

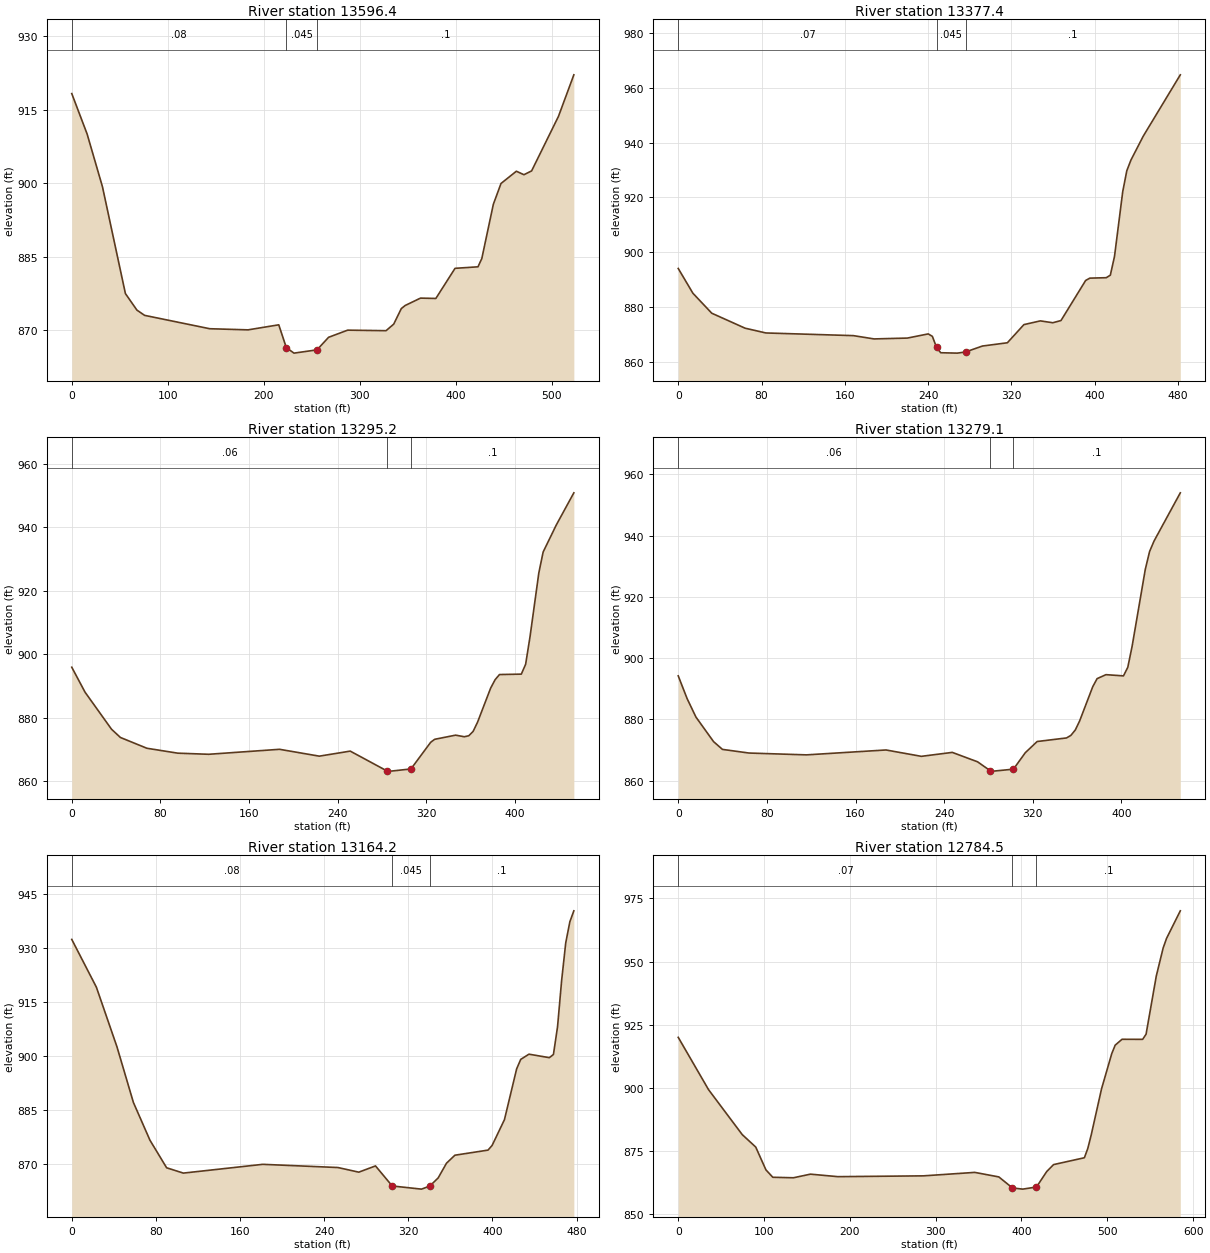
Type RM Length L Ch R = 1 ,13596.4 ,219.7,219,218.1
XS GIS Cut Line= 2
     1774383.117      353775.726     1774370.096       354298.73
#Sta/Elev= 30
       0  918.26      16  910.01      32  899.23    55.9  877.44    67.9  874.06
    75.9  872.99   143.8  870.26   183.7  870.03   215.7  871.06   223.6  866.39
   231.6  865.28   255.6  865.95   267.6  868.51   287.5  869.97   327.5  869.86
   335.5   871.2   343.4  874.37   347.4     875   363.4  876.51   379.4  876.44
   399.4  882.59   423.3   882.9   427.3  884.59   439.3  895.66   447.3  899.91
   463.3  902.41   471.2   901.7   479.2  902.48   507.2  913.62   523.2  922.09
#Mann= 3 , 0 , 0
       0     .08       0   223.6    .045       0   255.6      .1       0
Bank Sta=223.6,255.6
XS Rating Curve= 0 ,0
Exp/Cntr=0.3,0.1

Type RM Length L Ch R = 1 ,13377.4 ,88.3,82.2,76.4
XS GIS Cut Line= 4
     1774159.593      353814.789     1774159.593      353843.001
     1774174.784       354142.48     1774179.124       354296.56
#Sta/Elev= 30
       0  894.14    14.1  885.12    32.2  877.85    64.2   872.4    84.2  870.66
   168.2  869.69   188.1  868.49   220.1   868.8   240.1  870.32   244.1  869.42
   248.1  865.38   252.1  863.46   268.1  863.32   276.1  863.76   292.1   865.9
   316.1  867.09     332   873.7   347.8  875.06   359.7  874.38   367.6  875.18
   391.3  889.78   395.3  890.62   411.1  890.78     415  891.71     419  898.54
   426.9  922.12   430.8  929.71   434.8  933.62   446.6  942.31   482.2  964.64
#Mann= 3 , 0 , 0
       0     .07       0   248.1    .045       0   276.1      .1       0
Bank Sta=248.1,276.1
XS Rating Curve= 0 ,0
Exp/Cntr=0.3,0.1

Type RM Length L Ch R = 1 ,13295.2 ,15.8,16,15.7
XS GIS Cut Line= 6
     1774074.865       353829.91     1774092.226      354088.591
     1774095.241      354102.781     1774105.073      354133.556
     1774109.761      354161.681     1774130.594      354278.348
#Sta/Elev= 30
       0   895.9      12  888.02    35.9  876.34    43.9  873.75    67.8  870.35
    95.7   868.8   123.6  868.45   187.5  870.02   223.4  867.86   251.3  869.45
   284.5  863.19   288.1  863.14   306.1  863.83   323.9  872.23   327.5  873.17
   346.4  874.48   354.3  873.98   358.3   874.3   362.2  875.66   366.2  878.57
     378  889.29     382  891.94     386  893.59   405.7  893.72   409.6  896.83
   413.6  905.62   421.5  925.64   425.4  932.23   437.3  940.77   453.1  950.88
#Mann= 3 , 0 , 0
       0     .06       0   284.5    .045       0   306.1      .1       0
Bank Sta=284.5,306.1
XS Rating Curve= 0 ,0
Exp/Cntr=0.3,0.1

Type RM Length L Ch R = 1 ,13279.1 ,110.3,115,119.4
XS GIS Cut Line= 6
     1774060.282       353836.16     1774077.643      354094.841
     1774080.658      354109.031      1774090.49      354139.806
     1774095.177      354167.931     1774116.011      354284.598
#Sta/Elev= 30
       0  894.21       8  886.79      16  880.74    31.9  872.72    39.9  870.19
    63.8     869   115.7   868.4   187.5     870   219.4  867.92   247.3  869.21
   270.1  866.14   281.7  863.19   284.5  863.09   302.5  863.73   313.2   869.1
   323.9  872.76   350.4  873.93   354.3  874.75   358.3  876.51   362.2  879.44
   374.1  890.68     378   893.3     386   894.6   401.8   894.2   405.7     897
   409.6  903.86   421.5  928.99   425.4  934.86   429.4  938.26   453.1     954
#Mann= 3 , 0 , 0
       0     .06       0   281.7    .045       0   302.5      .1       0
Bank Sta=281.7,302.5
XS Rating Curve= 0 ,0
Exp/Cntr=0.3,0.1

Type RM Length L Ch R = 1 ,13164.2 ,377.8,379.7,381.4
XS GIS Cut Line= 4
     1773938.239      353806.108      1773951.26      353871.213
     1773975.131      354188.053     1773975.131      354281.369
#Sta/Elev= 30
       0  932.38    23.4  919.09      43  902.47    58.6  887.01    74.3  876.52
    90.2  868.82   106.1  867.34   181.6  869.78   253.1  868.89   272.9   867.6
   288.8  869.34   304.7  863.76   332.5  862.88   340.4  863.72   348.4     866
   356.3  870.09   364.3  872.32   395.8  873.74   399.7  875.05   411.4   882.2
     423  896.34   426.9  898.99   434.7  900.44   454.1  899.47     458  900.36
   461.9  908.07   465.8  920.98   469.7  931.44   473.6  937.28   477.4  940.34
#Mann= 3 , 0 , 0
       0     .08       0   304.7    .045       0   340.4      .1       0
Bank Sta=304.7,340.4
XS Rating Curve= 0 ,0
Exp/Cntr=0.3,0.1

Type RM Length L Ch R = 1 ,12784.5 ,445.6,445.1,444.9
XS GIS Cut Line= 3
     1773636.589      353780.067     1773595.357      353860.362
     1773593.187      354355.154
#Sta/Elev= 30
       0  920.06    35.3  899.38    74.6  881.58    90.3  876.67   102.2  867.64
   110.2  864.71   134.2  864.51   154.1  865.94     186  864.95   285.8  865.27
   345.6  866.64   373.6  864.85   389.5  860.49   401.5  860.02   417.5  860.86
   429.4  866.97   437.4  869.72   473.3  872.43   477.3  876.12   481.3  881.49
   493.3  899.68   505.2  913.61   509.2  916.96   517.2  919.29   541.2  919.26
   545.2   921.3   557.1  944.29   565.1   955.4   569.1  959.22   585.1   970.1
#Mann= 3 , 0 , 0
       0     .07       0   389.5    .045       0   417.5      .1       0
Bank Sta=389.5,417.5
XS Rating Curve= 0 ,0
Exp/Cntr=0.3,0.1

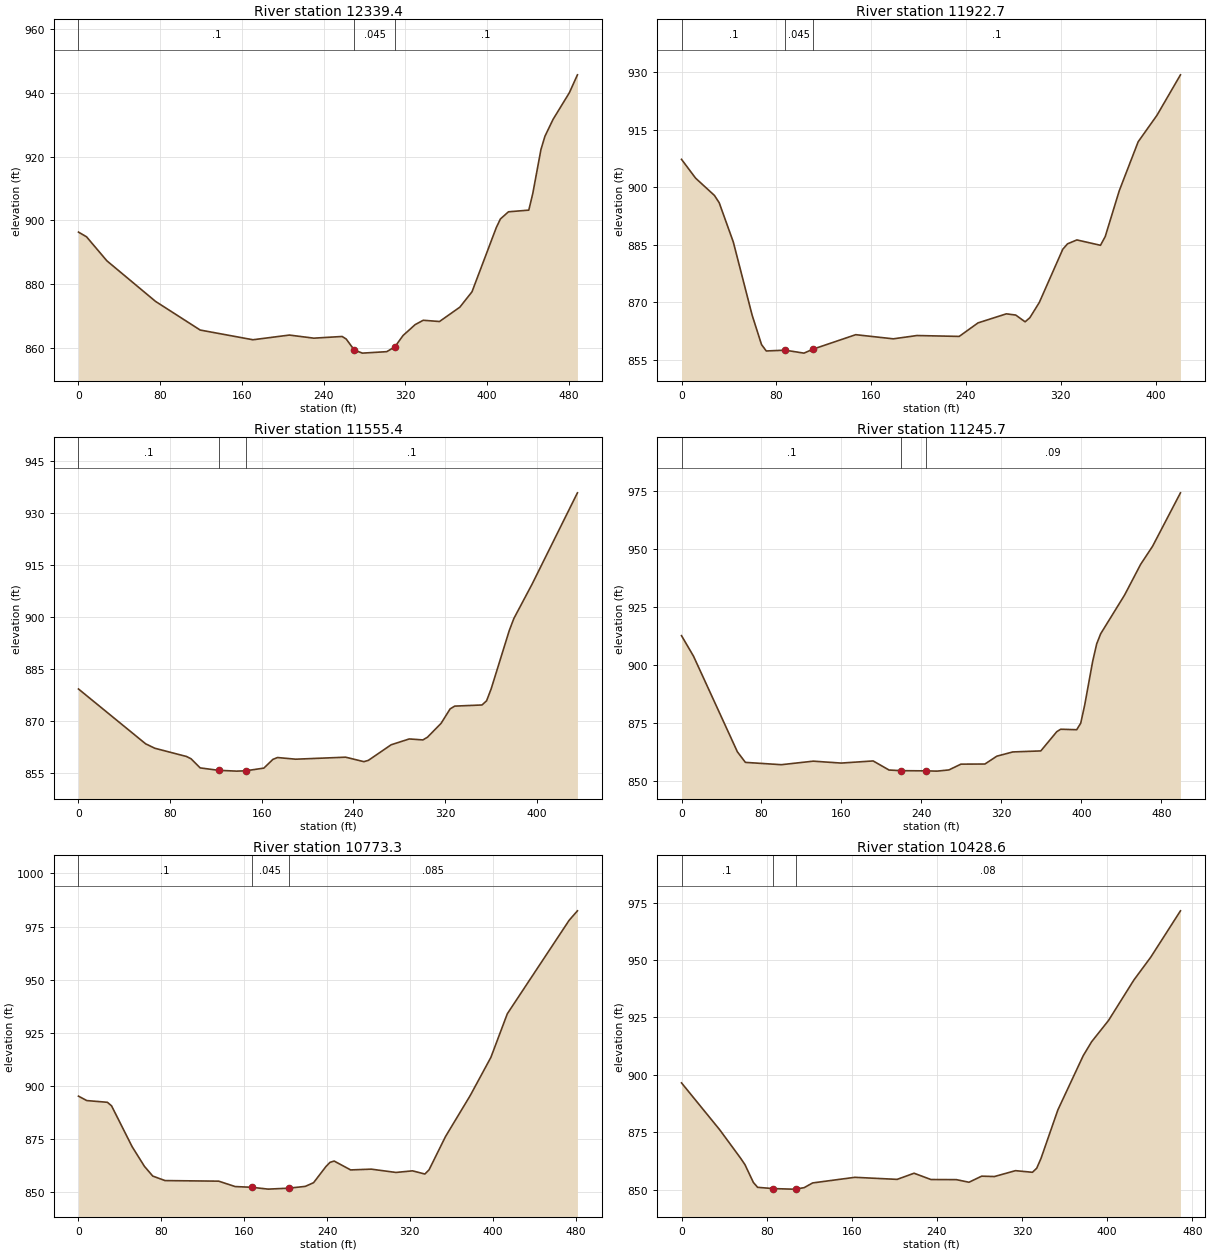
Type RM Length L Ch R = 1 ,12339.4 ,416.1,416.7,416.3
XS GIS Cut Line= 2
     1773148.308      353858.192     1773152.649      354346.473
#Sta/Elev= 30
       0   896.3     7.9  894.82    27.8  887.28    75.4  874.54   119.1  865.54
   170.7  862.49   206.4  863.96   230.3  862.99     258  863.52     262  862.72
     270  859.22   277.9  858.29   301.7  858.75   309.6  860.25   317.6  863.81
   329.5  867.25   337.4  868.61   353.3  868.22   373.2  872.72   385.1  877.55
   408.9  897.73   412.9  900.42   420.8  902.68   440.7   903.2   444.6  908.43
   452.6  922.26   456.5  926.41   464.5  931.74   480.4  940.08   488.3   945.7
#Mann= 3 , 0 , 0
       0      .1       0     270    .045       0   309.6      .1       0
Bank Sta=270,309.6
XS Rating Curve= 0 ,0
Exp/Cntr=0.3,0.1

Type RM Length L Ch R = 1 ,11922.7 ,366.4,367.2,366.4
XS GIS Cut Line= 2
     1772772.874      353888.574     1772770.704      354309.581
#Sta/Elev= 30
       0   907.3    11.9  902.39    27.8  897.88    31.8  895.98    43.7  885.74
    59.6  866.64    67.5  858.99    71.5  857.31    87.4  857.52   103.3  856.75
   111.2  857.81     147  861.56   178.7  860.48   198.6  861.34   234.3  861.11
   250.2  864.64   274.1     867     282  866.68   289.9  864.92   293.9  865.98
   301.9  869.97   321.7  883.85   325.7  885.26   333.6  886.28   353.5  884.88
   357.5  887.15   369.4  899.15   385.3  911.88   401.2  918.81     421  929.35
#Mann= 3 , 0 , 0
       0      .1       0    87.4    .045       0   111.2      .1       0
Bank Sta=87.4,111.2
XS Rating Curve= 0 ,0
Exp/Cntr=0.3,0.1

Type RM Length L Ch R = 1 ,11555.4 ,309.7,309.7,310.5
XS GIS Cut Line= 3
     1772429.992      353929.806     1772412.631      353968.869
     1772412.631      354361.664
#Sta/Elev= 30
       0   879.1    58.6  863.29    66.6  862.01    94.3  859.63    98.3  858.96
   106.2  856.34   122.3  855.64     138  855.41   145.9   855.5   161.8  856.28
   169.7   858.8   173.7  859.33   189.6  858.85   233.2  859.43   249.1  858.14
     253  858.51   272.9  863.01   288.7  864.69   300.6  864.41   304.6  865.19
   316.5   869.2   324.4  873.37   328.4  874.16   352.2  874.49   356.2   875.7
   360.2  879.14     376  895.96     380  899.43   395.9  909.33   435.5  935.68
#Mann= 3 , 0 , 0
       0      .1       0   122.3    .045       0   145.9      .1       0
Bank Sta=122.3,145.9
XS Rating Curve= 0 ,0
Exp/Cntr=0.3,0.1

Type RM Length L Ch R = 1 ,11245.7 ,473.9,472.5,471.5
XS GIS Cut Line= 2
     1772119.662      353914.615     1772117.492      354413.747
#Sta/Elev= 30
       0  912.57      12  903.73    55.9  862.51    63.9  857.96    99.8  856.96
   131.8  858.48   159.7  857.66   191.7  858.58   207.6  854.66   219.6  854.39
   244.4   854.3   255.6  854.19   267.5  854.71   279.5   857.2   303.5  857.25
   315.4  860.63   331.4  862.46   359.4   862.9   375.4   871.2   379.3  872.24
   395.3  872.04   399.3  874.82   403.3  882.66   411.3  901.54   415.3  909.05
   419.3   913.4   443.2  930.08   459.2  943.26   471.2   951.1   499.1  974.13
#Mann= 3 , 0 , 0
       0      .1       0   219.6    .045       0   244.4     .09       0
Bank Sta=219.6,244.4
XS Rating Curve= 0 ,0
Exp/Cntr=0.3,0.1

Type RM Length L Ch R = 1 ,10773.3 ,342.5,344.7,344
XS GIS Cut Line= 2
     1771685.635      353908.105     1771679.124      354389.876
#Sta/Elev= 30
       0  895.19       8  893.11    27.9   892.3    31.9  890.66    51.8  871.41
    63.7  862.14    71.7  857.58    83.6  855.45   135.4  855.18   151.3  852.64
   167.2   852.3   183.2  851.43   203.1  851.88     219  852.72     227  854.46
   238.9  862.03   242.9  864.04   246.9  864.64   262.8  860.47   282.7  860.83
   306.6  859.28   322.5  860.04   334.5  858.54   338.5  860.51   354.4  876.17
   378.3   895.5   398.2  913.42   414.1  933.98   473.8  977.97   481.8  982.42
#Mann= 3 , 0 , 0
       0      .1       0   167.2    .045       0   203.1    .085       0
Bank Sta=167.2,203.1
XS Rating Curve= 0 ,0
Exp/Cntr=0.3,0.1

Type RM Length L Ch R = 1 ,10428.6 ,385.2,376,363.8
XS GIS Cut Line= 2
     1771366.624      353892.914     1771366.624      354361.664
#Sta/Elev= 30
       0  896.49    35.8   876.1    55.6   863.6    59.6  860.85    67.5   853.1
    71.5  850.95    85.9  850.41   103.3  850.17   107.3  850.17   115.2  850.81
   123.2  852.87   162.9  855.32   202.6  854.42   218.5   857.1   234.4  854.35
   258.2  854.31   270.1  853.17     282  855.82     294  855.66   313.8  858.22
   329.7  857.51   333.7  859.26   337.7  863.47   353.6  884.68   377.4  908.32
   385.3  914.41   401.2   923.7     425  941.32   440.9   951.3   468.8   971.5
#Mann= 3 , 0 , 0
       0      .1       0    85.9    .045       0   107.3     .08       0
Bank Sta=85.9,107.3
XS Rating Curve= 0 ,0
Exp/Cntr=0.3,0.1

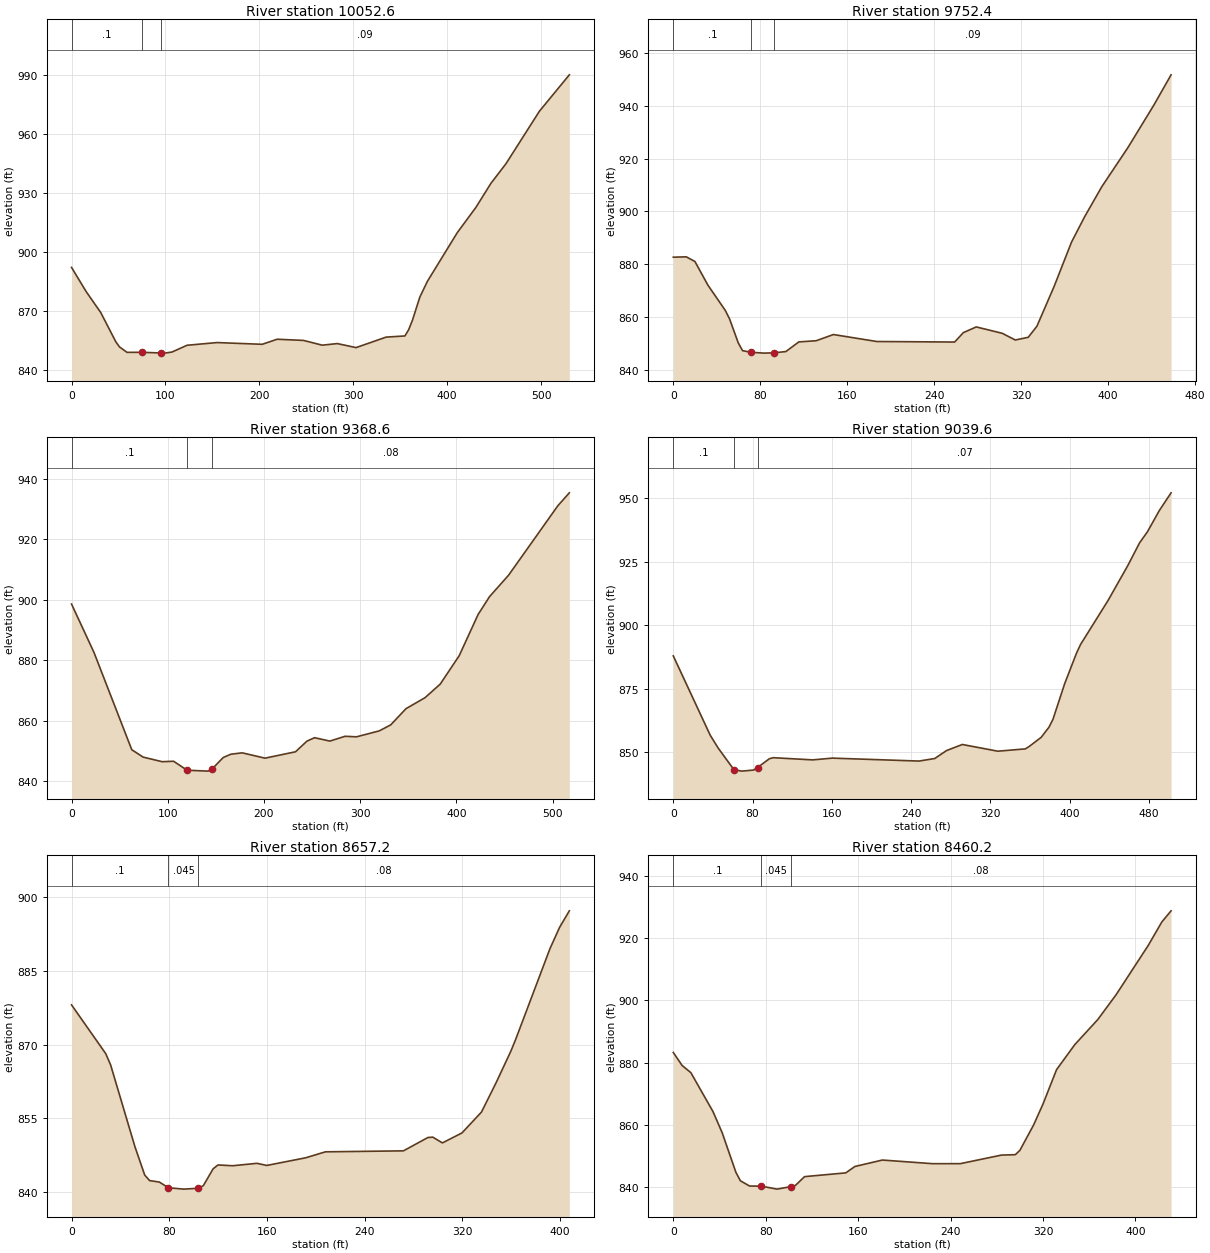
Type RM Length L Ch R = 1 ,10052.6 ,305.2,300.2,295.6
XS GIS Cut Line= 4
     1770960.808      353929.806     1770973.829      353958.018
     1771117.058      354261.838     1771156.121      354420.258
#Sta/Elev= 30
       0  892.09    15.5  879.81    31.1  869.07    47.1   854.2    51.1  851.53
    59.1  848.77    75.3  848.79      95  848.46      99  848.38     107  848.94
     123  852.39     155  853.77     203  852.88     219  855.47     247  854.86
     267  852.44     283  853.25     303   851.2     335  856.55     355  857.14
     359  860.32     363  865.12   370.9  876.97   378.9  884.96   410.7  909.78
   430.6  922.72   446.6  934.99   462.5  944.91   498.3  971.81   530.1  990.34
#Mann= 3 , 0 , 0
       0      .1       0    75.3    .045       0      95     .09       0
Bank Sta=75.3,95
XS Rating Curve= 0 ,0
Exp/Cntr=0.3,0.1

Type RM Length L Ch R = 1 ,9752.4  ,378.7,383.8,389.2
XS GIS Cut Line= 2
     1770689.541      354088.226     1770980.339      354441.959
#Sta/Elev= 30
       0  882.65      12  882.78    19.9  881.02    31.9  872.03    47.8  862.52
    51.8  859.25    59.7  850.26    63.7  847.25    71.7  846.63    83.6  846.32
    92.7  846.44   103.5  846.91   115.5  850.57   131.4  851.01   147.3  853.36
   187.2  850.72   258.8  850.52   266.8  854.08   278.7  856.24   302.6  853.83
   314.6  851.29   326.5  852.31   334.5  856.51   350.4  871.66   366.3  888.34
   378.3  897.91   394.2  909.36   418.1  924.09     442   940.2   457.9  951.71
#Mann= 3 , 0 , 0
       0      .1       0    71.7    .045       0    92.7     .09       0
Bank Sta=71.7,92.7
XS Rating Curve= 0 ,0
Exp/Cntr=0.3,0.1

Type RM Length L Ch R = 1 ,9368.6  ,330.7,329,326.7
XS GIS Cut Line= 4
     1770385.721      354264.008     1770403.083       354303.07
     1770533.291      354569.997     1770691.711      354650.292
#Sta/Elev= 30
       0  898.59    23.3   882.6    62.6   850.4    74.4  847.96    94.2  846.44
   106.1  846.59   120.1  843.62   141.7  843.32   145.7   843.9   157.6  847.81
   165.5  848.91   177.4  849.37   201.1  847.61   232.8  849.72   244.7  853.25
   252.6  854.38   268.5  853.26   284.3  854.85   296.2  854.67   319.9  856.64
   331.8  858.64   347.6  863.98   367.4  867.62   383.2  872.11   402.9  881.49
   422.6  895.16   434.5  901.07   454.2  908.12   505.5  931.14   517.4   935.4
#Mann= 3 , 0 , 0
       0      .1       0   120.1    .045       0   145.7     .08       0
Bank Sta=120.1,145.7
XS Rating Curve= 0 ,0
Exp/Cntr=0.3,0.1

Type RM Length L Ch R = 1 ,9039.6  ,382.3,382.4,382.5
XS GIS Cut Line= 3
     1770100.565      354405.935     1770108.378      354442.393
     1770347.961      354840.831
#Sta/Elev= 30
       0  887.85    37.3  856.58    45.2  851.62    61.1  843.08    69.1  842.48
      81   842.9      85   843.9    96.9  847.36   100.9  847.77   140.6  846.91
   160.5   847.6   247.9  846.44   263.8  847.45   275.7  850.58   291.6  852.97
   327.4  850.33   355.2  851.24   359.2  852.23   371.1  855.77     379  859.77
     383  862.84   394.9  876.97   406.8  888.95   410.8   892.3   438.6  909.67
   458.5  923.39   470.4  932.36   478.4  936.76   490.3  945.07   502.2  952.07
#Mann= 3 , 0 , 0
       0      .1       0    61.1    .045       0      85     .07       0
Bank Sta=61.1,85
XS Rating Curve= 0 ,0
Exp/Cntr=0.3,0.1

Type RM Length L Ch R = 1 ,8657.2  ,197.4,197,196.7
XS GIS Cut Line= 2
     1769771.919      354617.523     1769980.253      354967.784
#Sta/Elev= 30
       0  878.03      28  868.14      32  865.85    51.9  849.27    59.9  843.53
    63.9  842.41    71.9  842.11    79.3  840.96    91.9  840.68   103.9  840.86
   107.9  841.39   115.9   844.8   119.9  845.58   131.8  845.42   151.8  845.91
   159.8  845.48   191.8  847.04   207.8  848.24   271.7  848.44   291.7  851.14
   295.7  851.22   303.6  850.05   319.6  852.07   335.6  856.31   347.6  862.28
   359.6  868.63   363.6  871.05   391.6   889.4   399.5  893.74   407.5   897.1
#Mann= 3 , 0 , 0
       0      .1       0    79.3    .045       0   103.9     .08       0
Bank Sta=79.3,103.9
XS Rating Curve= 0 ,0
Exp/Cntr=0.3,0.1

Type RM Length L Ch R = 1 ,8460.2  ,202.3,201.5,200.7
XS GIS Cut Line= 3
     1769610.461      354732.107     1769626.086      354758.148
     1769835.721      355099.294
#Sta/Elev= 30
       0  883.28     7.6  879.12    15.2   876.8    34.3  864.34    42.3  857.51
    54.2  844.77    58.1  842.06      66  840.39    76.3  840.34    89.8  839.39
   101.7  840.19   105.7  840.58   113.6   843.4   149.3  844.61   157.2  846.67
     181  848.73   224.6  847.56   248.4  847.57   284.1  850.33     296  850.45
     300  851.87   311.8  859.98   319.8  866.58   331.7  877.77   347.5  885.82
   367.4  893.87   383.2  901.82     411  917.64   422.8  925.21   430.8  928.78
#Mann= 3 , 0 , 0
       0      .1       0    76.3    .045       0   101.7     .08       0
Bank Sta=76.3,101.7
XS Rating Curve= 0 ,0
Exp/Cntr=0.3,0.1

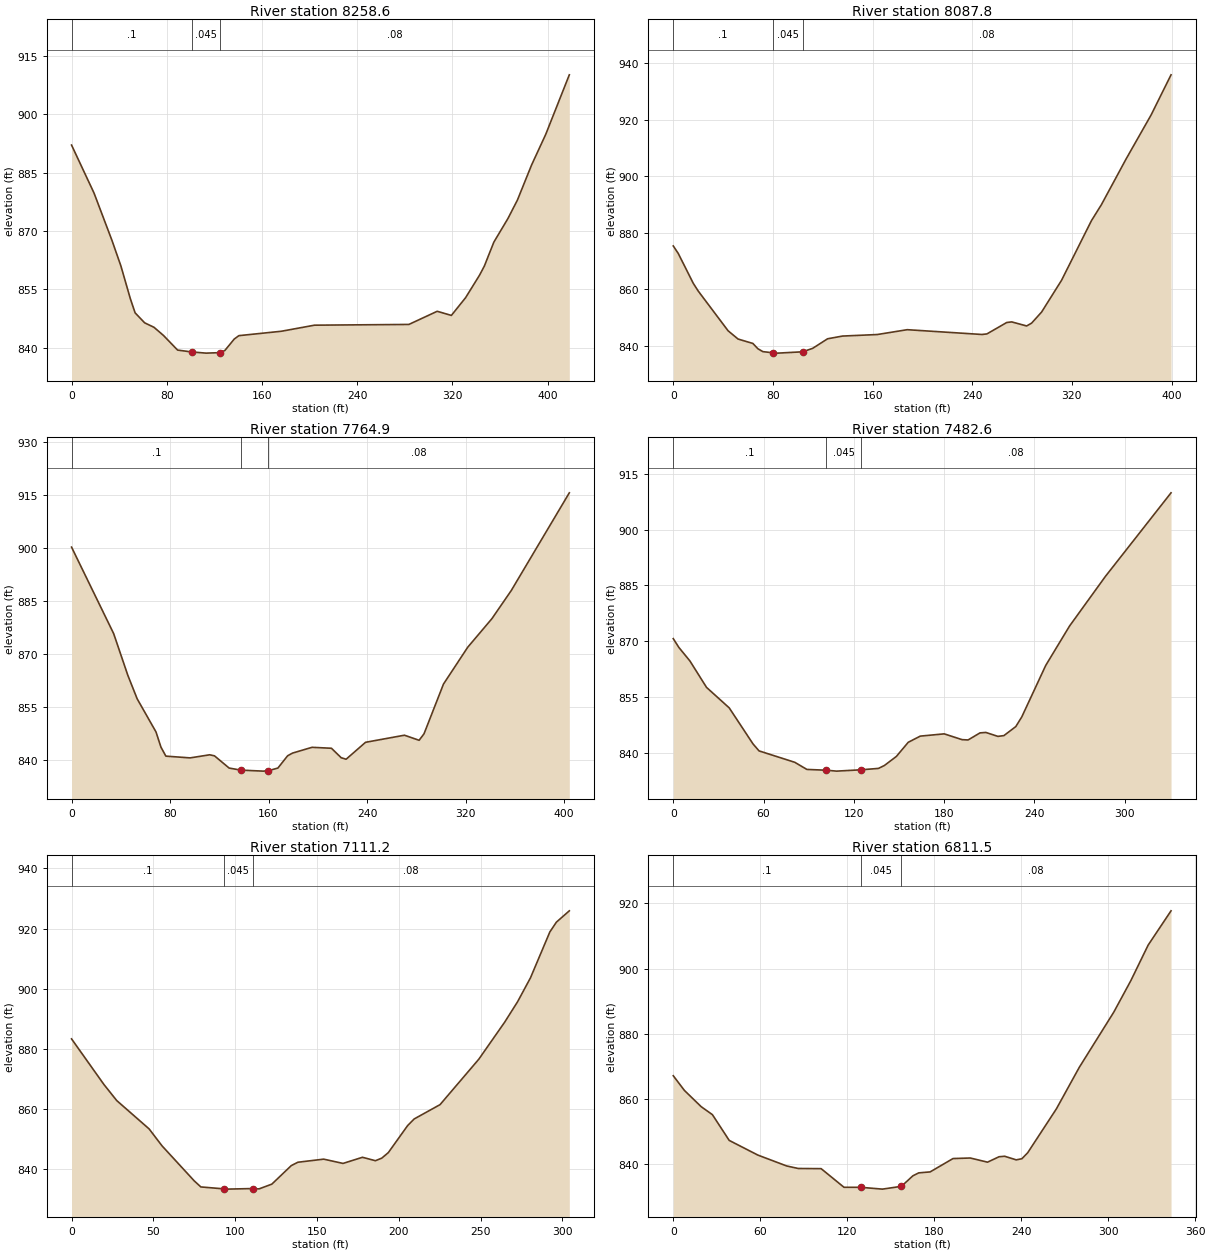
Type RM Length L Ch R = 1 ,8258.6  ,171.5,170.8,170.1
XS GIS Cut Line= 3
     1769422.961      354829.763     1769450.305      354861.013
     1769658.638      355174.815
#Sta/Elev= 30
       0  892.07    18.9  879.73      34  867.54    41.5  860.97    49.4  852.59
    53.4  848.96    61.4   846.4    69.3  845.24    77.2  843.16    89.1  839.39
   100.8  838.92   112.9  838.61   124.8  838.73   128.8  839.29   136.7  842.23
   140.6   843.1   176.3  844.23   204.1  845.79   283.4  845.98   307.2  849.36
   319.1   848.3     331  852.83   342.8  858.65   346.8  860.97   354.8  867.13
   366.6  873.18   374.6  877.94   386.5  886.95   398.4  894.83   418.2  910.12
#Mann= 3 , 0 , 0
       0      .1       0   100.8    .045       0   124.8     .08       0
Bank Sta=100.8,124.8
XS Rating Curve= 0 ,0
Exp/Cntr=0.3,0.1

Type RM Length L Ch R = 1 ,8087.8  ,323.7,322.9,322.2
XS GIS Cut Line= 2
     1769303.169      354950.857      1769534.94      355276.377
#Sta/Elev= 30
       0  875.38       4  872.73      16  862.22      20  859.46      44  845.41
      52  842.49    63.9  840.93    67.9  839.07    71.9  838.04    79.9  837.63
    83.9  837.51   103.9  837.98   111.9   839.2   123.9  842.58   135.9  843.54
   163.8  844.08   187.8  845.79   247.8   844.1   251.8   844.3   267.7  848.33
   271.7  848.54   283.7  847.11   287.7  848.12   295.7  852.03   311.7  863.24
   335.7  884.31   343.7  889.96   363.6  906.17   383.6  921.66   399.6  935.84
#Mann= 3 , 0 , 0
       0      .1       0    79.9    .045       0   103.9     .08       0
Bank Sta=79.9,103.9
XS Rating Curve= 0 ,0
Exp/Cntr=0.3,0.1

Type RM Length L Ch R = 1 ,7764.9  ,279.9,282.2,285.4
XS GIS Cut Line= 4
     1769023.525      355151.508     1769077.909      355186.534
     1769226.346      355381.846     1769305.774      355432.627
#Sta/Elev= 30
       0  900.23    34.2  875.72    45.7  863.91    53.3  857.23    68.6  847.84
    72.6  843.55    76.6  840.99    96.3  840.49   112.2  841.37   116.1  841.07
     128  837.61   137.6  837.02   155.7  836.74   159.6  836.84   167.6  837.61
   175.5  841.09   179.4  841.84   195.3  843.49   211.1  843.22     219  840.54
     223  840.11   238.8  844.91   270.4  846.92   282.3  845.48   286.3  847.33
   302.1  861.42   321.8  871.86   341.4  879.94   357.1   887.9   404.3  915.62
#Mann= 3 , 0 , 0
       0      .1       0   137.6    .045       0   159.6     .08       0
Bank Sta=137.6,159.6
XS Rating Curve= 0 ,0
Exp/Cntr=0.3,0.1

Type RM Length L Ch R = 1 ,7482.6  ,372.2,371.4,369.2
XS GIS Cut Line= 3
     1768860.461       355340.18     1768874.784      355370.127
     1769032.336      355622.732
#Sta/Elev= 30
       0  870.64     3.7  868.29    11.1  864.62    22.1  857.53    37.2  852.01
      53  842.32      57  840.44    80.8  837.36    88.8  835.45   101.8  835.23
   108.6  834.99   124.5  835.34   136.4  835.72   140.4  836.52   148.3  838.94
   156.2  842.75   164.2  844.41   180.1  845.02     192  843.46     196  843.38
   203.9  845.28   207.8   845.4   215.8  844.34   219.8  844.55   227.7  846.98
   231.7   849.6   247.6  863.44   263.4  874.02   287.2  887.36   330.9  909.89
#Mann= 3 , 0 , 0
       0      .1       0   101.8    .045       0   124.5     .08       0
Bank Sta=101.8,124.5
XS Rating Curve= 0 ,0
Exp/Cntr=0.3,0.1

Type RM Length L Ch R = 1 ,7111.2  ,299.4,299.7,299.6
XS GIS Cut Line= 3
     1768583.117      355575.857     1768600.044      355620.127
     1768744.576      355832.367
#Sta/Elev= 30
       0   883.3    19.8  868.12    27.6  862.79    47.4  853.36    55.3  847.72
      75  836.06      79  834.06      93  833.42    94.8  833.33   110.6  833.52
   114.6  833.41   122.4  834.99   134.3  841.16   138.3  842.27   154.1   843.3
   165.9  841.88   177.8  843.92   185.7  842.78   189.6  843.64   193.6  845.48
   205.4  854.47   209.4  856.67   225.2  861.43   248.9  876.55   264.7  888.86
   272.6  895.67   280.5  903.65   292.3  918.86   296.3  922.12   304.2  925.89
#Mann= 3 , 0 , 0
       0      .1       0      93    .045       0   110.6     .08       0
Bank Sta=93,110.6
XS Rating Curve= 0 ,0
Exp/Cntr=0.3,0.1

Type RM Length L Ch R = 1 ,6811.5  ,237.5,237.1,236.8
XS GIS Cut Line= 3
     1768301.867      355711.273     1768322.701      355743.825
     1768493.274       355996.43
#Sta/Elev= 30
       0  867.06     7.7  862.54    19.3  857.54      27  855.11    38.6  847.19
    58.4  842.68    78.2  839.35    86.2  838.57     102  838.52   117.8  832.79
   129.3  832.79   144.3  832.23   157.4  833.09   165.3  836.32   169.3  837.22
   177.2  837.52     193  841.62   204.9  841.79   216.8  840.51   224.7  842.17
   228.6  842.33   236.6  841.22   240.5  841.57   244.5   843.4   264.3  856.88
   280.1  869.64   303.9   886.6   315.7   896.3   327.6  907.18   343.4  917.72
#Mann= 3 , 0 , 0
       0      .1       0   129.3    .045       0   157.4     .08       0
Bank Sta=129.3,157.4
XS Rating Curve= 0 ,0
Exp/Cntr=0.3,0.1

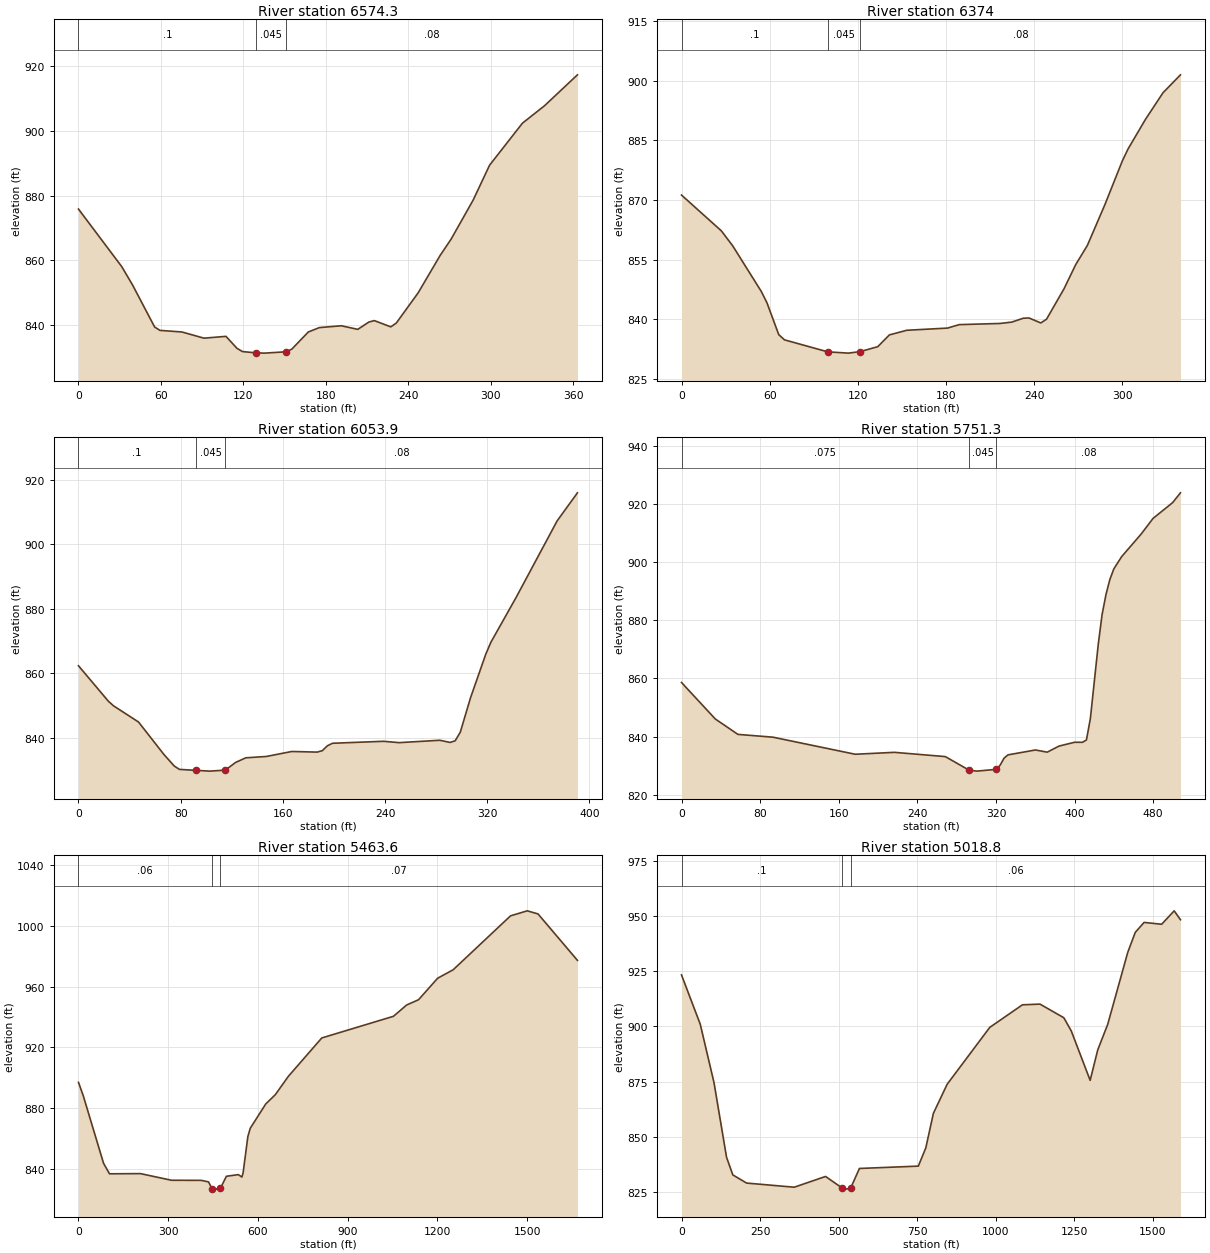
Type RM Length L Ch R = 1 ,6574.3  ,201,200.4,199.6
XS GIS Cut Line= 3
     1768114.367      355859.711     1768136.503      355892.263
     1768321.399      356157.888
#Sta/Elev= 30
       0  875.85    31.5  858.06    39.4  852.36    55.4  839.43    59.3  838.38
    75.3  837.89    91.3  835.98   107.3  836.54   115.3  832.84   119.3  831.84
   129.4  831.43   135.3  831.36   151.2  831.78   155.2  832.59   167.2  837.89
   175.2  839.24   191.2  839.81   203.2   838.7   211.2  840.94   215.2  841.41
   227.2  839.47   231.2  840.64   247.1  849.97   263.1  861.52   271.1  866.57
   287.1   878.6   299.1  889.41     323  902.38     339  907.74     363  917.31
#Mann= 3 , 0 , 0
       0      .1       0   129.4    .045       0   151.2     .08       0
Bank Sta=129.4,151.2
XS Rating Curve= 0 ,0
Exp/Cntr=0.3,0.1

Type RM Length L Ch R = 1 ,6374    ,311.2,320.1,326.9
XS GIS Cut Line= 3
     1767964.628      355948.252     1767973.742      355997.732
     1768141.711      356233.409
#Sta/Elev= 30
       0  871.26    27.1  862.27    34.8  858.52    54.3  847.03    58.2  844.14
    66.2  836.15    70.1  834.84    99.6  831.82   113.7   831.5   121.7  831.89
   133.6  833.12   141.5  836.08   153.4  837.25   181.1   837.8   189.1  838.67
   216.8  838.96   224.8   839.3   232.7  840.28   236.6  840.34   244.6  839.09
   248.5  840.03   260.4  847.67   268.4  853.78   276.3  858.58   288.2  868.81
   300.1  879.83     304  882.85   315.9  890.32   327.8  896.99   339.7  901.51
#Mann= 3 , 0 , 0
       0      .1       0    99.6    .045       0   121.7     .08       0
Bank Sta=99.6,121.7
XS Rating Curve= 0 ,0
Exp/Cntr=0.3,0.1

Type RM Length L Ch R = 1 ,6053.9  ,295.1,302.5,309.6
XS GIS Cut Line= 4
     1767693.794       356058.93     1767692.492      356101.898
     1767768.013      356350.596     1767777.128      356437.836
#Sta/Elev= 30
       0  862.33    23.4  851.34    27.4  849.92      47  844.89      67  834.77
      75  831.23      79   830.2    91.7   829.9     103  829.66     115  829.98
     123  832.36     131  833.79     147   834.2     167  835.75   186.9  835.56
   190.9  836.01   194.9  837.53   198.9   838.3   238.9  838.91   250.9  838.49
   282.9  839.23   290.9  838.56   294.9  839.07   298.9  841.74   306.9   852.4
   318.8  865.88   322.8  869.59   342.8  883.67   374.7  907.25   390.6  915.96
#Mann= 3 , 0 , 0
       0      .1       0    91.7    .045       0     115     .08       0
Bank Sta=91.7,115
XS Rating Curve= 0 ,0
Exp/Cntr=0.3,0.1

Type RM Length L Ch R = 1 ,5751.3  ,288.7,287.7,286
XS GIS Cut Line= 3
     1767463.326      355987.315      1767441.19      356048.513
     1767435.982      356491.221
#Sta/Elev= 30
       0  858.61    34.4  846.05    57.4  840.75      93  839.79   176.8  833.91
   216.6  834.57   268.5   833.1   292.4  828.48   300.4   828.1   320.4  828.71
   324.3  830.17   328.3  832.58   332.3   833.7   360.2  835.38   372.2  834.63
   384.2  836.72   400.1  838.04   408.1  838.02   412.1  838.84   416.1  846.18
   424.1  871.65     428  881.94     432  888.92     436  894.14     440  897.74
     448  901.97   467.9  909.77   479.9  915.11   499.8  920.54   507.8  923.92
#Mann= 3 , 0 , 0
       0    .075       0   292.4    .045       0   320.4     .08       0
Bank Sta=292.4,320.4
XS Rating Curve= 0 ,0
Exp/Cntr=0.3,0.1

Type RM Length L Ch R = 1 ,5463.6  ,432,444.8,456.9
XS GIS Cut Line= 4
      1767141.32      355872.081      1767159.55      356458.018
     1767242.883      356616.872     1766979.254      357480.067
#Sta/Elev= 30
       0  897.09      16  888.29    83.8  843.98   103.7  837.07   207.4  837.19
   311.1  832.83   410.8  832.76   434.7  831.76   446.6  827.28   458.6  827.01
   474.6  827.56   494.5  835.44   534.4  836.53   546.3  834.94   550.3   837.6
   566.3  861.52   574.3  866.95   626.1  882.92     658  888.99   701.8  901.08
   813.5  926.25  1053.2  940.48  1097.1  947.88    1137  951.35  1200.9  965.47
  1252.8  971.03  1444.5 1006.41  1500.4 1009.71  1536.4 1007.68  1668.2   977.2
#Mann= 3 , 0 , 0
       0     .06       0   446.6    .045       0   474.6     .07       0
Bank Sta=446.6,474.6
XS Rating Curve= 0 ,0
Exp/Cntr=0.3,0.1

Type RM Length L Ch R = 1 ,5018.8  ,340.3,352,363.2
XS GIS Cut Line= 4
     1767025.869      355776.595     1766973.786      355846.907
     1766637.848      356422.428      1766289.15      357180.588
#Sta/Elev= 30
       0  923.26    59.7  900.94   103.5  874.48   143.4  840.74   163.3  832.78
   207.2  829.08   358.8  827.21   458.6  832.07   511.1  826.88   522.4  826.34
   538.4  826.78   566.4  835.69   753.9  836.75   777.8  845.04   801.8  860.61
   845.7  873.81   981.5  899.55  1085.3  909.74  1141.2  910.06  1217.1  903.89
    1241  897.86  1300.9  875.56  1324.9  889.28  1356.8   900.9  1420.7  933.53
  1444.6  942.53  1472.6  947.03  1528.5  946.19  1568.4  952.27  1588.4  948.24
#Mann= 3 , 0 , 0
       0      .1       0   511.1    .045       0   538.4     .06       0
Bank Sta=511.1,538.4
XS Rating Curve= 0 ,0
Exp/Cntr=0.3,0.1