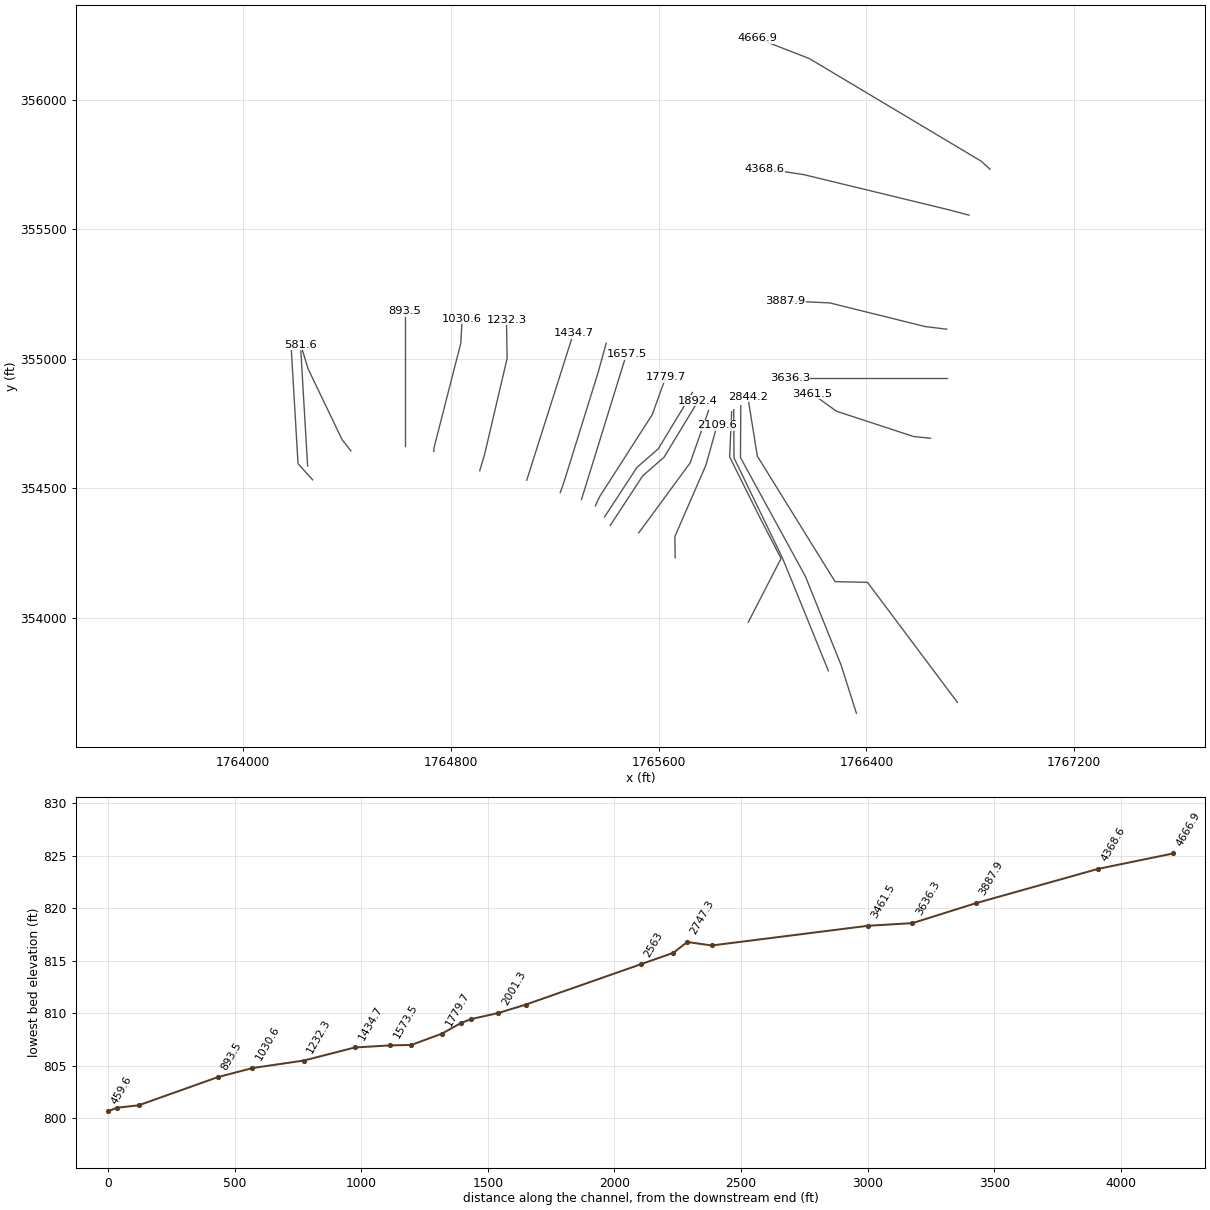
HEC-RAS study WESTFK.prj: WESTFK

--- WESTFK.g01 (geometry) --- (continued)

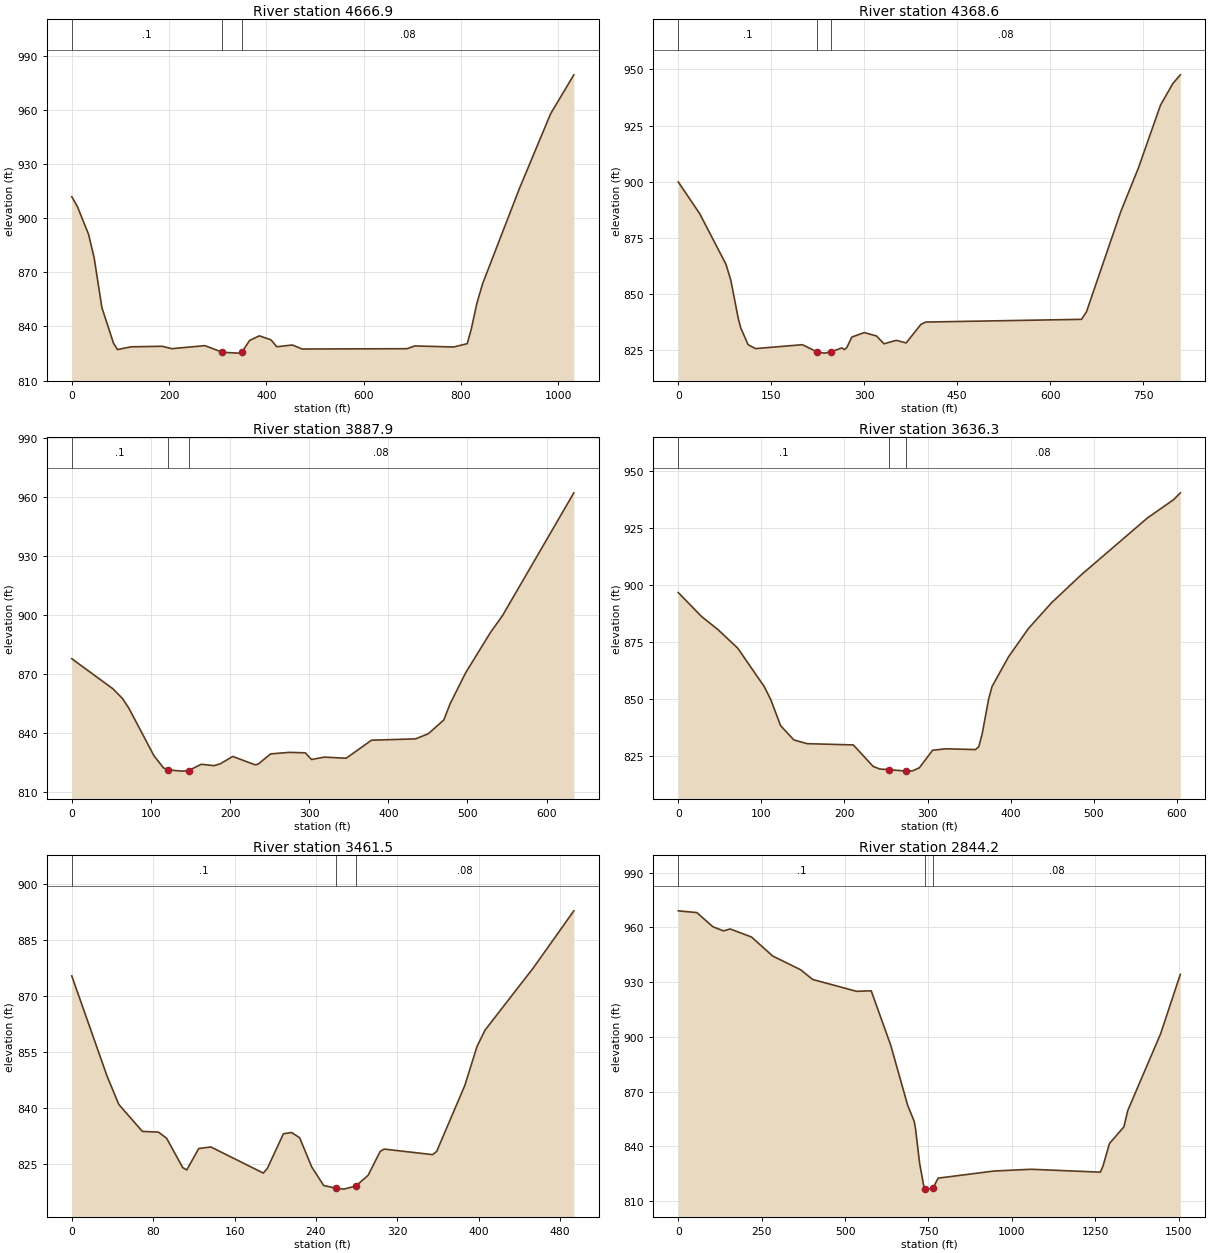
Type RM Length L Ch R = 1 ,4666.9  ,291.3,298.2,304.7
XS GIS Cut Line= 4
     1766875.695      355731.456     1766841.841      355762.706
     1766180.383      356158.539     1765979.862      356236.664
#Sta/Elev= 30
       0   911.9    11.5  906.56    34.6  891.02    46.1  877.92      62   850.4
      86   830.6      94  827.21     122  828.74   185.9  829.04   205.8  827.71
   273.7  829.39   309.7  825.73   341.6  825.24   349.6  825.72   365.6  832.27
   385.6  834.83   409.5  832.61   421.5  828.77   453.5  829.75   473.4  827.52
   689.1  827.69   705.1  829.23     785  828.64   812.9  830.47   820.9  838.12
   832.9  853.02   844.8   863.9   920.5  916.65   984.3  957.87  1032.1  979.47
#Mann= 3 , 0 , 0
       0      .1       0   309.7    .045       0   349.6     .08       0
Bank Sta=309.7,349.6
XS Rating Curve= 0 ,0
Exp/Cntr=0.3,0.1

Type RM Length L Ch R = 1 ,4368.6  ,480.7,480.7,480.7
XS GIS Cut Line= 4
     1766794.966      355554.372     1766716.841      355575.206
      1766159.55      355710.622     1766005.904       355734.06
#Sta/Elev= 30
       0  899.97    34.6  885.84      77  863.32    84.8  856.24    96.8  839.24
   100.8  835.03   112.7  827.52   124.7  825.78   200.3  827.51   224.2  824.26
   236.2  823.76   246.8   824.4   264.1  826.08     268  825.33     272  826.29
     280   830.9   299.9   832.9   319.8   831.4   331.8  827.92   351.7  829.45
   367.6   828.3   391.5  836.57   399.5  837.59   650.4   838.8   658.4  842.11
   714.1  886.98     742     906   777.9  934.15   797.8  943.74   809.8  947.61
#Mann= 3 , 0 , 0
       0      .1       0   224.2    .045       0   246.8     .08       0
Bank Sta=224.2,246.8
XS Rating Curve= 0 ,0
Exp/Cntr=0.3,0.1

Type RM Length L Ch R = 1 ,3887.9  ,242.1,251.6,257.9
XS GIS Cut Line= 4
     1766709.029      355114.268     1766625.695      355124.685
     1766258.508      355215.831     1766086.633      355223.643
#Sta/Elev= 30
       0  877.73      52  862.41      64  857.52      72  852.64   103.9   828.3
   115.8  822.21   121.5  821.13   139.7   820.5   147.7  820.79   163.6  823.99
   179.6  823.29   187.5  824.21   203.4  827.98   231.3  823.77   235.3  823.97
   251.2  829.27   275.1  830.05     295  829.82     303  826.41     319  827.63
   346.8  827.07   378.7  836.24   434.4  836.92   450.4   839.5   470.1  846.54
     478  854.73   497.5  870.43   528.8  890.93   544.4  899.76   634.4  962.17
#Mann= 3 , 0 , 0
       0      .1       0   121.5    .045       0   147.7     .08       0
Bank Sta=121.5,147.7
XS Rating Curve= 0 ,0
Exp/Cntr=0.3,0.1

Type RM Length L Ch R = 1 ,3636.3  ,185.4,174.8,166.3
XS GIS Cut Line= 2
     1766709.029      354926.768     1766104.862      354926.768
#Sta/Elev= 30
       0  896.84    27.8  886.42    47.7  880.62    71.6  872.46   103.4  855.68
   111.3  849.97   123.2  838.51   139.1  832.27     155  830.62   210.7  830.07
   234.5  820.68   242.5  819.51   253.7  819.23   274.3  818.59   282.2  818.73
   290.2  820.06   306.1  827.73     322  828.38   357.7  828.03   361.7  829.31
   365.7  834.81   373.6  850.26   377.6  855.61   397.5  868.67   421.3     881
   449.2  892.33   484.9  904.55   564.4  929.42   596.2  937.52   604.2   940.5
#Mann= 3 , 0 , 0
       0      .1       0   253.7    .045       0   274.3     .08       0
Bank Sta=253.7,274.3
XS Rating Curve= 0 ,0
Exp/Cntr=0.3,0.1

Type RM Length L Ch R = 1 ,3461.5  ,632.5,617.4,600.3
XS GIS Cut Line= 4
     1766647.223      354693.608     1766582.119      354700.119
      1766284.81      354797.775     1766191.494      354865.049
#Sta/Elev= 30
       0  875.34    34.6  848.62    46.2  840.99    69.4  833.77    85.2  833.58
    93.2  831.95     109  824.11     113  823.46   124.8   829.2   136.7  829.61
   188.2  822.63   192.2  823.88     208  833.14     216  833.47   223.9  832.09
   235.8  824.28   247.6   819.3   259.5   818.6   267.4  818.34   279.3  819.19
   291.2  822.03   303.1  828.43   307.1  829.04   354.6  827.56   358.6  828.42
   386.3  846.08   398.2  856.45   406.1  860.83   453.7  877.52   493.4  892.73
#Mann= 3 , 0 , 0
       0      .1       0   259.5    .045       0   279.3     .08       0
Bank Sta=259.5,279.3
XS Rating Curve= 0 ,0
Exp/Cntr=0.3,0.1

Type RM Length L Ch R = 1 ,2844.2  ,100.3,96.9,92.8
XS GIS Cut Line= 5
     1766750.695      353674.164     1766404.275      354137.438
     1766279.341       354140.31     1765979.862      354624.685
     1765943.404      354853.851
#Sta/Elev= 30
       0  969.14    55.8  968.17   103.7  960.43   135.6  958.14   155.6  959.18
   219.4  954.81   283.2  944.34     367  936.79   402.9  931.49   534.6  924.97
   578.5  925.26     637   895.4   687.8  862.41   707.4  853.63   711.4  849.51
   723.4  830.85   735.3   818.8   739.3  816.72   747.2  816.46   763.2  816.93
   779.1  822.49   946.4  826.38  1057.9  827.35    1265  825.77  1272.9  828.92
  1292.6   841.5  1335.8  850.59  1347.6  859.62    1446  901.71    1505  934.26
#Mann= 3 , 0 , 0
       0      .1       0   739.3    .045       0   763.2     .08       0
Bank Sta=739.3,763.2
XS Rating Curve= 0 ,0
Exp/Cntr=0.3,0.1

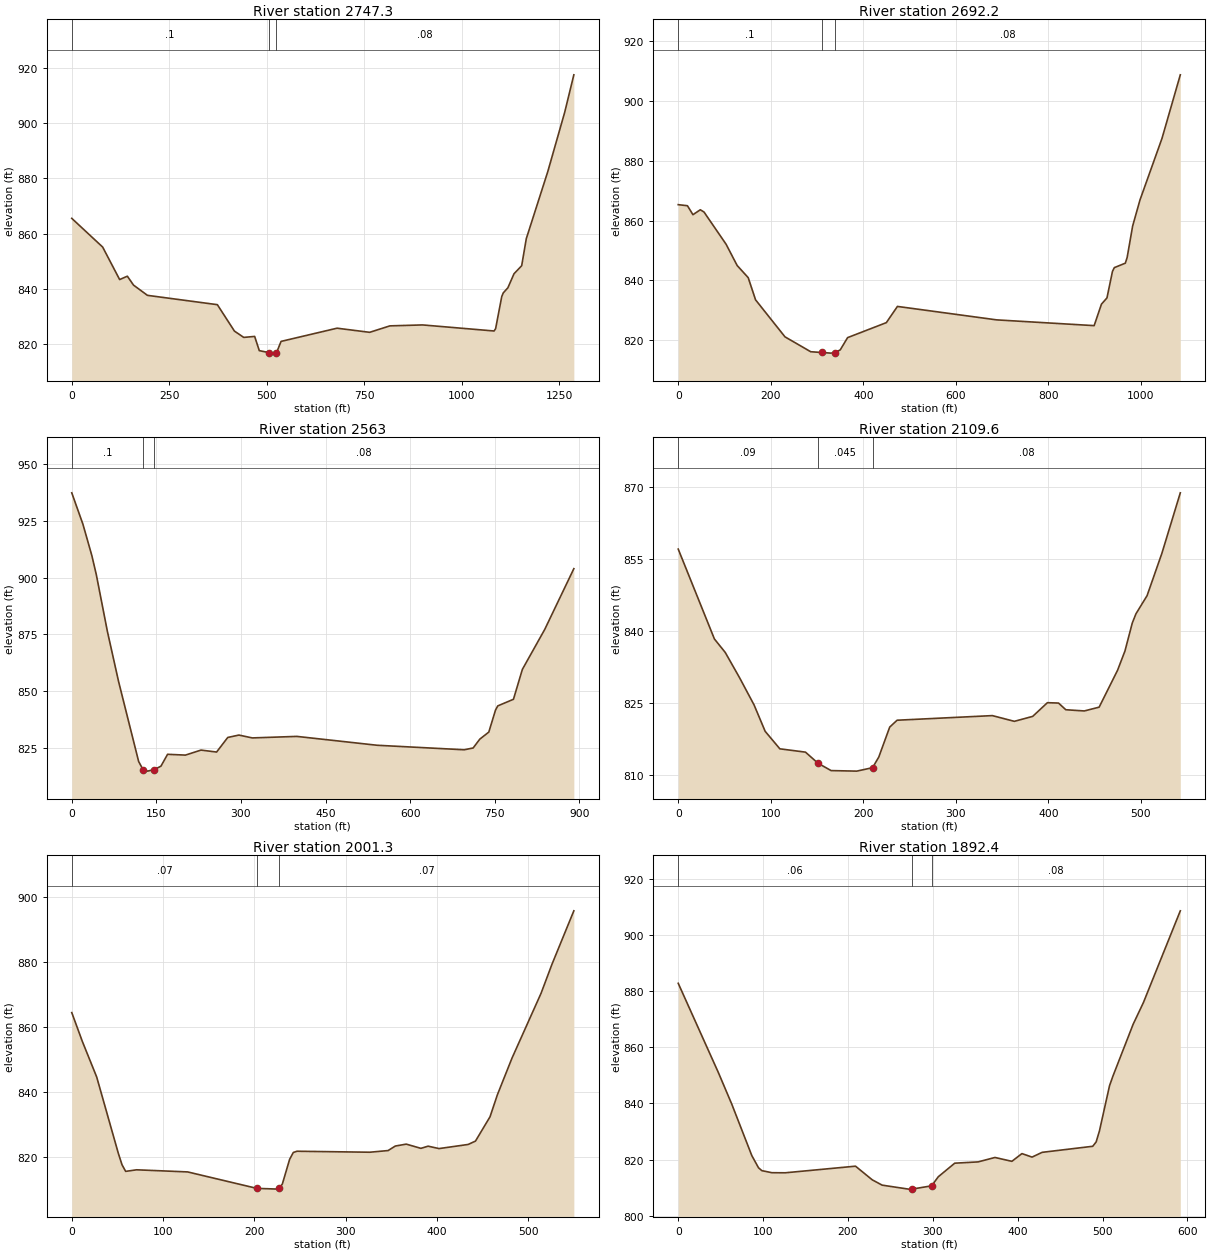
Type RM Length L Ch R = 1 ,2747.3  ,55,55,55.3
XS GIS Cut Line= 5
     1766361.633      353631.976     1766303.039      353816.872
     1766165.018      354160.622     1765915.018      354618.956
      1765916.32      354819.476
#Sta/Elev= 30
       0   865.5    79.2  855.12   122.7  843.38   142.5  844.59   158.3  841.37
     194  837.67   373.2   834.3     417  824.75   440.9  822.47   468.8  822.83
   480.7  817.69   504.6     817   520.6  816.79   524.6  816.84   536.5  821.03
     680   825.8   763.6  824.31   815.5  826.64   899.2  826.98  1082.5  824.79
  1086.5  825.64  1102.2  837.24  1106.1  838.56  1117.9   840.4  1133.6  845.47
  1153.3  848.38  1165.1  858.15  1220.2  882.39  1263.4  903.74    1287  917.37
#Mann= 3 , 0 , 0
       0      .1       0   504.6    .045       0   524.6     .08       0
Bank Sta=504.6,524.6
XS Rating Curve= 0 ,0
Exp/Cntr=0.3,0.1

Type RM Length L Ch R = 1 ,2692.2  ,149,129.2,109.2
XS GIS Cut Line= 5
      1766253.56      353796.039     1766111.633      354146.299
     1766075.175      354234.841     1765890.279      354617.654
     1765888.977      354803.851
#Sta/Elev= 30
       0  865.29    19.9  864.93    31.8  861.94    47.7  863.58    55.7  862.83
   103.4  852.09   127.3     845   151.2  840.94   167.1  833.54   230.7  821.19
   286.4  816.22   310.4  815.97   330.2  815.76   338.1  815.89   350.1  816.84
     366  820.93   449.7  825.93   473.7  831.34   688.2  826.85   898.8  824.93
   914.6   832.1   926.5  834.18   938.4  843.03   942.4  844.28   966.2  845.77
   970.1  847.66     982  858.16   997.8  866.83  1045.4  887.39    1085   908.6
#Mann= 3 , 0 , 0
       0      .1       0   310.4    .045       0   338.1     .08       0
Bank Sta=310.4,338.1
XS Rating Curve= 0 ,0
Exp/Cntr=0.3,0.1

Type RM Length L Ch R = 1 ,2563    ,446.8,453.4,456.9
XS GIS Cut Line= 5
     1765944.966      353983.539     1766071.268      354229.633
     1765987.935      354391.091     1765873.352       354621.56
     1765881.164      354796.039
#Sta/Elev= 30
       0  937.44    19.8  923.58    35.6  909.76    43.5  901.37    63.2  876.26
      83  854.21   118.6   818.9   126.4  815.31   134.4  814.66   146.2  815.34
   158.1  816.84   169.9  822.08   201.5  821.73   229.2  823.94   256.8  823.08
   276.6  829.51   296.4  830.57   320.1  829.31   399.1  829.98   541.5  826.07
   695.9  824.08   711.7  824.87   723.6  828.78   739.5  831.88   751.4   841.6
   755.4  843.44   783.2  846.35     799  859.53   838.7  877.18   890.3  903.98
#Mann= 3 , 0 , 0
       0      .1       0   126.4    .045       0   146.2     .08       0
Bank Sta=126.4,146.2
XS Rating Curve= 0 ,0
Exp/Cntr=0.3,0.1

Type RM Length L Ch R = 1 ,2109.6  ,117.5,108.2,100.6
XS GIS Cut Line= 4
     1765663.716      354232.237     1765662.414      354314.268
     1765782.206       354590.31     1765825.175      354743.956
#Sta/Elev= 30
       0  857.01    39.1  838.31    50.8  835.51    66.4  830.21      82  824.57
    93.9  819.11   109.8  815.46   137.5  814.77     151 812.465   165.2  810.93
   192.9  810.82     210 811.541   216.7  813.75   228.5  819.98   236.5  821.41
   339.4  822.37   363.2  821.18     383  822.21   398.9  825.06   410.9  824.98
   418.8  823.59   438.8  823.34   454.8  824.13   474.7   831.8   482.7  835.82
   490.6  841.63   494.6  843.56   506.6  847.33   522.6  856.14   542.5  868.72
#Mann= 3 , 0 , 0
       0     .09       0     151    .045       0     210     .08       0
Bank Sta=151,210
XS Rating Curve= 0 ,0
Exp/Cntr=0.3,0.1

Type RM Length L Ch R = 1 ,2001.3  ,114,109,103.7
XS GIS Cut Line= 4
     1765523.091      354328.591     1765546.529      354359.841
     1765721.008      354598.122     1765792.622      354801.247
#Sta/Elev= 30
       0  864.31    11.7  855.36    27.3   844.5      51  821.02      55  817.54
      59  815.48      71  815.96   126.9  815.31   202.7  810.25   226.6  810.02
   227.4 810.336   230.6   811.6   238.6  819.21   242.6  821.29   246.6  821.67
   326.4  821.37   346.4  821.88   354.3  823.27   366.3  823.86   382.3  822.56
   390.2  823.23   402.2  822.49   434.1  823.76   442.1   824.8     458  832.26
     466  838.98     482  850.26   513.9  870.25   525.8  879.14   549.8  895.61
#Mann= 3 , 0 , 0
       0     .07       0   202.7    .045       0   227.4     .07       0
Bank Sta=202.7,227.4
XS Rating Curve= 0 ,0
Exp/Cntr=0.3,0.1

Type RM Length L Ch R = 1 ,1892.4  ,39.4,39.5,39.4
XS GIS Cut Line= 4
     1765413.716      354357.237     1765538.716      354548.643
     1765620.747      354620.258     1765752.258      354837.706
#Sta/Elev= 30
       0  882.89    47.3  851.03    63.1  839.76    86.7   821.4    94.6  817.05
    98.5  816.03   110.4  815.29   126.1  815.26   208.9  817.62   228.6  812.75
   240.3  810.85   271.4  809.43   275.5  809.44   298.6  810.61   306.4  813.84
   325.8  818.69   353.4  819.15   373.2  820.73   393.1  819.35     405  822.11
   416.9  820.86   428.8  822.56   488.4  824.72   492.4  826.25   496.3  830.18
   508.2  846.34   512.2  849.76     536  868.26     548  875.93   591.6  908.76
#Mann= 3 , 0 , 0
       0     .06       0   275.5    .045       0   298.6     .08       0
Bank Sta=275.5,298.6
XS Rating Curve= 0 ,0
Exp/Cntr=0.3,0.1

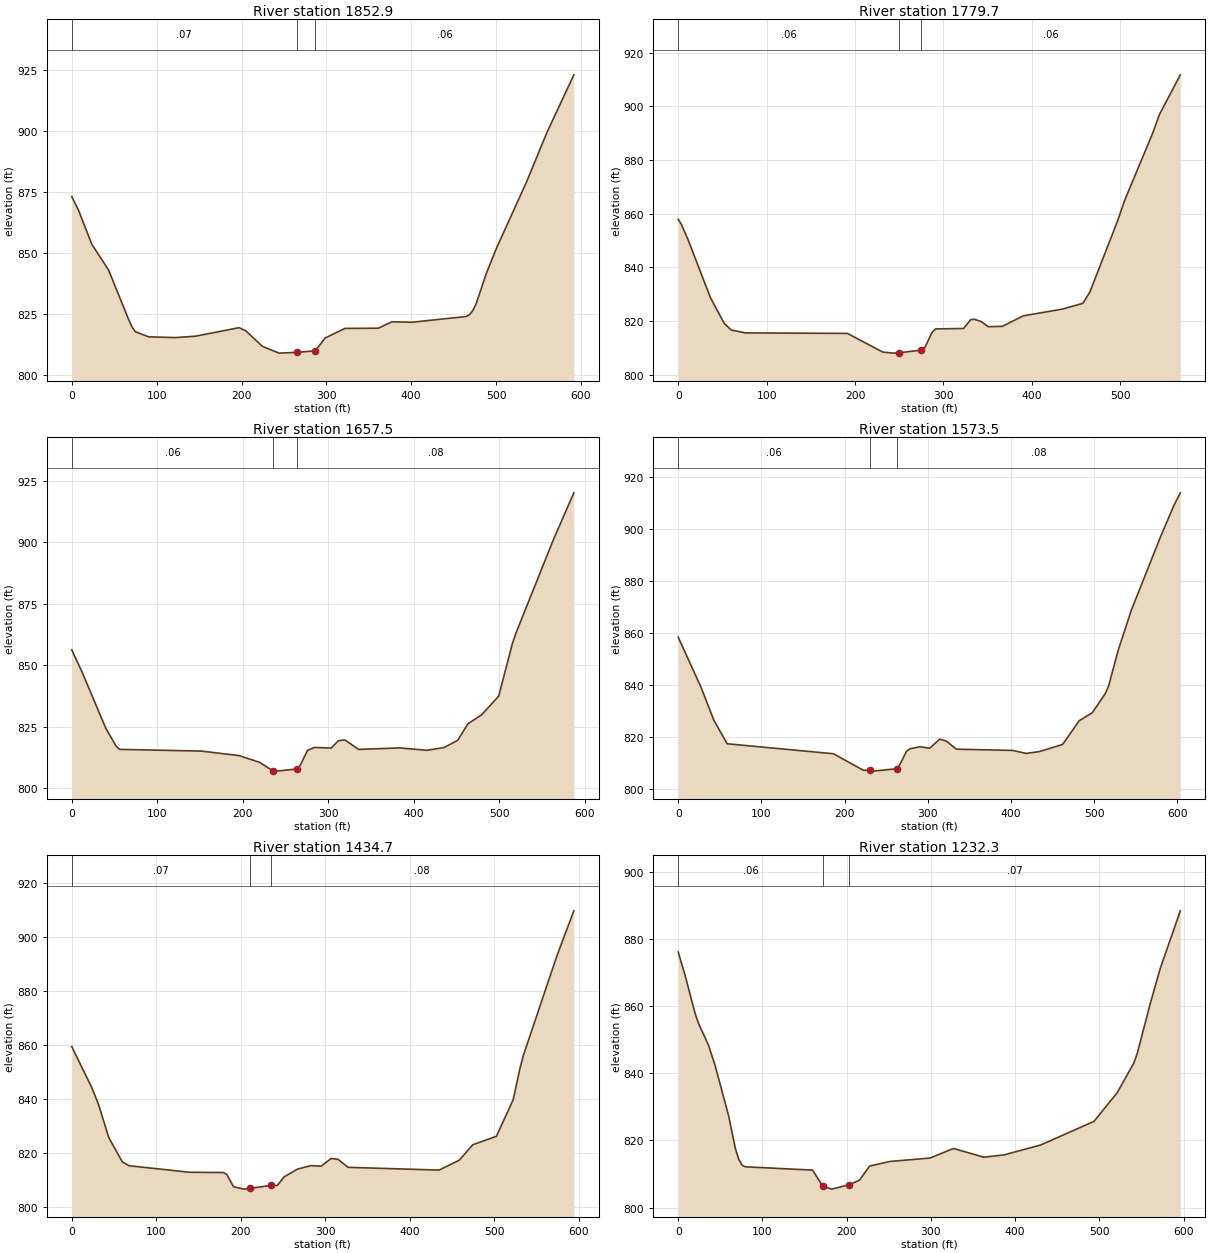
Type RM Length L Ch R = 1 ,1852.9  ,66.8,73.2,79.6
XS GIS Cut Line= 4
     1765391.581      354389.789     1765516.581      354581.195
     1765598.612       354652.81     1765730.122      354870.258
#Sta/Elev= 30
       0  873.19     7.9  867.64    23.6  853.65    43.4   843.1      67  822.82
      71  819.76    74.9  817.82    90.6  815.73   122.2  815.42   145.8  815.98
   197.1  819.48     205   818.2   224.7  811.82   244.2  809.05   265.2  809.37
   286.9     810   298.6  815.25   321.9  819.18   361.3  819.26   377.2  821.89
     401  821.71   464.6  824.05   468.5  824.78   472.5  826.44   476.5   829.3
   488.4  841.61   500.3  851.94     536   879.3   559.9  899.46   591.6  923.08
#Mann= 3 , 0 , 0
       0     .07       0   265.2    .045       0   286.9     .06       0
Bank Sta=265.2,286.9
XS Rating Curve= 0 ,0
Exp/Cntr=0.3,0.1

Type RM Length L Ch R = 1 ,1779.7  ,115.9,122.2,128.1
XS GIS Cut Line= 4
     1765356.425      354432.758     1765373.352      354469.216
     1765575.175       354784.32     1765627.258      354928.851
#Sta/Elev= 30
       0   857.9     3.6     856      11  850.42    36.5  828.66    52.1  819.12
    60.1  816.64      76   815.6   191.5   815.4   231.3  808.46   243.2  808.06
   249.8  808.17   275.1  809.19     279  810.11     287  815.72     291  817.08
   322.8  817.24   330.8  820.52   334.8  820.68   342.7  819.84   350.7   817.9
   366.6  818.04   390.5  821.96   434.1  824.43   457.7  826.59   465.6  830.74
   497.1  857.35     505  864.93   536.5  889.78   544.4  896.93     568  911.71
#Mann= 3 , 0 , 0
       0     .06       0   249.8    .045       0   275.1     .06       0
Bank Sta=249.8,275.1
XS Rating Curve= 0 ,0
Exp/Cntr=0.3,0.1

Type RM Length L Ch R = 1 ,1657.5  ,84,84,83.9
XS GIS Cut Line= 2
     1765303.039      354457.497     1765476.216      355018.695
#Sta/Elev= 30
       0  856.25      12  847.27      40  824.26    51.9  817.12    55.9  815.81
   151.8  815.11   195.8  813.27   219.7  810.54   235.7  807.01   239.7  806.97
   263.7  807.85   267.7  809.63   275.7  815.38   283.7  816.58   303.6  816.36
   311.6  819.22   315.6  819.55   319.6   819.6   335.6  815.79   383.6  816.41
   415.5  815.44   435.5  816.56   451.5  819.52   463.5  826.24   479.4  829.83
   499.4  837.46   515.4  858.78   519.4   862.9   563.3  900.92   587.3  920.03
#Mann= 3 , 0 , 0
       0     .06       0   235.7    .045       0   263.7     .08       0
Bank Sta=235.7,263.7
XS Rating Curve= 0 ,0
Exp/Cntr=0.3,0.1

Type RM Length L Ch R = 1 ,1573.5  ,139.1,138.8,138.5
XS GIS Cut Line= 4
     1765221.008      354483.539     1765235.331      354523.904
     1765366.841      354947.081     1765398.091      355060.362
#Sta/Elev= 30
       0  858.43    27.3  839.24    42.8  826.53    58.8  817.45   186.6  813.61
   222.5  807.26   230.5  807.28   234.5  806.93   262.4  807.85   266.4  809.42
   274.4   814.6   278.4  815.48   290.4  816.31   302.3  815.75   314.3  819.23
   322.3  818.48   334.3  815.38   402.1  814.88   418.1  813.74   434.1  814.45
     462  817.19     482  826.32   497.7  829.37   513.4  836.79   517.3  839.65
   529.1  853.69   544.7  868.87     580  897.25   595.6  908.94   603.5  913.94
#Mann= 3 , 0 , 0
       0     .06       0   230.5    .045       0   262.4     .08       0
Bank Sta=230.5,262.4
XS Rating Curve= 0 ,0
Exp/Cntr=0.3,0.1

Type RM Length L Ch R = 1 ,1434.7  ,200.6,202.4,204.2
XS GIS Cut Line= 2
     1765092.102      354531.716     1765271.789      355098.122
#Sta/Elev= 30
       0  859.39    23.9   844.1    31.9  837.78    43.9  825.71    59.8  816.81
    67.8  815.37   139.6  812.96   179.5  812.86   183.4  812.19   191.4  807.63
   203.4  806.73   211.4     807   235.3  808.11   243.3  808.09   251.2  811.22
   267.2  814.15   283.2  815.42   295.1   815.2   307.1  818.08   315.1  817.74
     327  814.79   434.7  813.76   458.6  817.41   474.6  823.13   502.5  826.24
   522.4  839.76   530.4   851.3   534.4  856.05   574.3  893.04   594.2  909.55
#Mann= 3 , 0 , 0
       0     .07       0   211.4    .045       0   235.3     .08       0
Bank Sta=211.4,235.3
XS Rating Curve= 0 ,0
Exp/Cntr=0.3,0.1

Type RM Length L Ch R = 1 ,1232.3  ,201.7,201.7,200.8
XS GIS Cut Line= 4
     1764911.112      354568.174     1764929.341      354629.372
     1765016.581      355001.768     1765013.977      355151.508
#Sta/Elev= 30
       0  876.13       8  869.33      20  857.87      24  854.94    35.9  848.41
    43.9  842.23    59.9  827.24    67.8  817.64    71.8  814.38    75.8  812.63
    79.8  812.13   159.5  811.15   171.4  806.44   182.2  805.48   203.3  806.82
   215.2  808.16   227.2  812.35   251.1  813.72   298.9  814.74   326.8   817.6
   362.7     815   386.6  815.67   430.4  818.64   493.6  825.67   521.2  834.23
   540.9  843.03   544.9  845.85   560.6  860.95   572.4  871.34   596.1  888.42
#Mann= 3 , 0 , 0
       0     .06       0   171.4    .045       0   203.3     .07       0
Bank Sta=171.4,203.3
XS Rating Curve= 0 ,0
Exp/Cntr=0.3,0.1

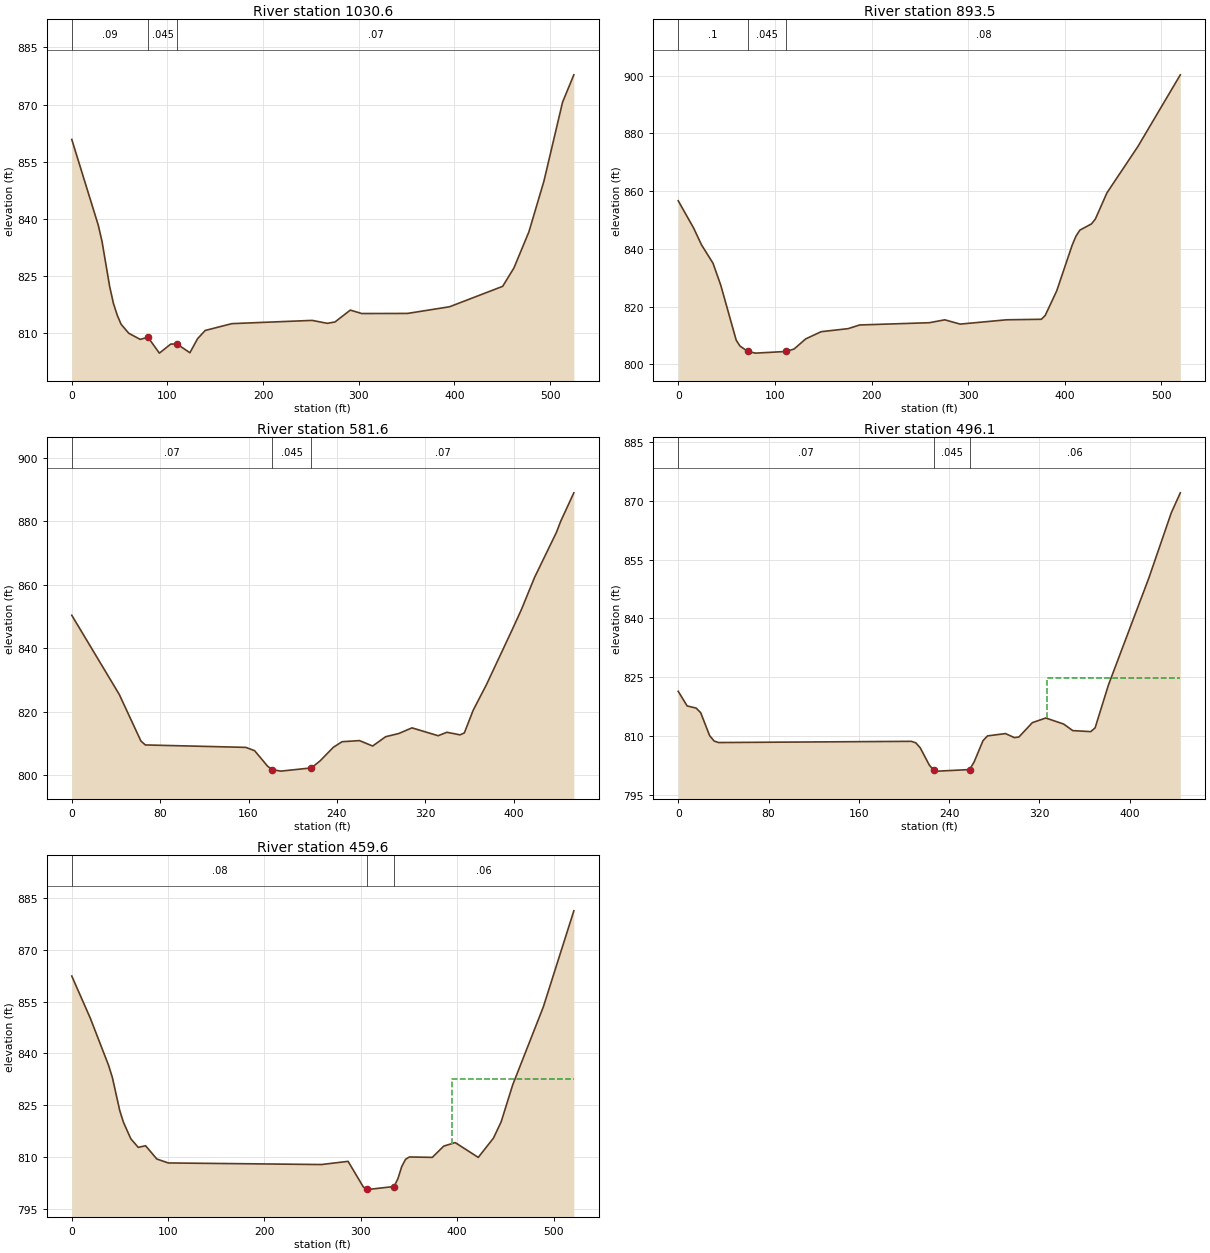
Type RM Length L Ch R = 1 ,1030.6  ,131.2,137.1,142.7
XS GIS Cut Line= 4
     1764734.029      354642.393     1764735.331      354658.018
     1764838.195      355060.362     1764843.404      355154.112
#Sta/Elev= 30
       0  860.85    27.7  838.35    31.6  834.13    39.6  822.28    43.6  817.78
    47.6  814.68    51.6  812.34    59.6  809.98    71.6  808.37    79.6  808.96
    91.6  804.77   103.5  807.15   110.1  807.15   123.5  804.87   131.5  808.55
   139.5  810.72   167.4  812.51   251.3  813.36   267.2  812.59   275.2  812.95
   291.2  816.06   303.2  815.16   351.1  815.19     395  816.94   450.5   822.3
   462.3  827.14   477.9  836.59   493.6  849.88   513.1  870.62   524.9   877.8
#Mann= 3 , 0 , 0
       0     .09       0    79.6    .045       0   110.1     .07       0
Bank Sta=79.6,110.1
XS Rating Curve= 0 ,0
Exp/Cntr=0.3,0.1

Type RM Length L Ch R = 1 ,893.5   ,298.6,311.9,323
XS GIS Cut Line= 2
      1764622.05      354664.529      1764622.05       355184.06
#Sta/Elev= 30
       0  856.65      16  847.16      24  841.44      36  835.01      44  827.43
      60  808.37    63.9  806.36    71.9   804.5    79.9   803.9   111.9  804.48
   119.9  805.33   131.9  808.83   147.9  811.32   175.8  812.38   187.8  813.65
   259.8  814.43   275.8  815.43   291.7  813.95   339.7  815.44   375.7  815.62
   379.7  816.94   391.6  825.44   407.6  841.28   411.6  844.44   415.6  846.49
   427.6  848.64   431.6  850.33   443.6   859.4   475.6  875.43   519.5  900.25
#Mann= 3 , 0 , 0
       0      .1       0    71.9    .045       0   111.9     .08       0
Bank Sta=71.9,111.9
XS Rating Curve= 0 ,0
Exp/Cntr=0.3,0.1

Type RM Length L Ch R = 1 ,581.6   ,96.6,85.5,74.9
XS GIS Cut Line= 4
     1764415.018      354644.997     1764381.164      354687.966
     1764249.654      354962.706      1764222.31      355053.851
#Sta/Elev= 30
       0  850.39      43  825.41    62.6  810.71    66.6  809.48   157.6  808.71
   165.5  807.66   177.3  802.75   181.3  801.71   189.2  801.22   216.9  802.24
   224.8  804.47   236.7  808.73   244.6   810.5   260.4  810.85   272.3  809.14
   284.1  812.08     296  813.09   307.9  814.87   331.6  812.39   339.5  813.48
   351.4  812.66   355.3  813.28   363.3  820.43   375.2  828.43     399  846.12
   406.9  852.15   418.8  862.29   438.6  876.51   442.6  880.12   454.4  889.01
#Mann= 3 , 0 , 0
       0     .07       0   181.3    .045       0   216.9     .07       0
Bank Sta=181.3,216.9
XS Rating Curve= 0 ,0
Exp/Cntr=0.3,0.1

Type RM Length L Ch R = 1 ,496.1   ,36.5,36.4,36.4
XS GIS Cut Line= 2
     1764248.352      354586.404      1764222.31      355030.414
#Sta/Elev= 30
       0  821.36     7.9  817.63    15.9  817.08    19.9   815.9    27.8  810.05
    31.8  808.67    35.7  808.28   206.5  808.59   210.5   808.2   214.4  806.93
   222.4  802.55   226.4  801.19   230.3  800.98   258.1  801.38   262.1   803.3
     270  808.76     274  809.98   289.9  810.57   297.8  809.54   301.8  809.69
   313.7  813.36   325.6  814.55   341.5     813   349.5  811.33   365.4  811.07
   369.3  812.02   381.2  823.04     417  850.36   436.8  866.96   444.8  872.06
#Mann= 3 , 0 , 0
       0     .07       0   226.4    .045       0   258.1     .06       0
#XS Ineff= 2 , 0
                           326.4          824.69
Permanent Ineff=
       F       F
Bank Sta=226.4,258.1
XS Rating Curve= 0 ,0
Exp/Cntr=0.3,0.1

Type RM Length L Ch R = 1 ,459.6   ,109.7,119.1,129.7
XS GIS Cut Line= 3
     1764267.883      354533.018     1764211.428      354595.644
     1764185.852      355031.716
#Sta/Elev= 30
       0  862.43    19.2  850.24    38.3  836.47    42.2  832.95    49.8  823.43
    53.7     820    61.3  815.24      69  812.76    76.6  813.23    88.3  809.38
   100.2  808.24     259  807.78   286.8   808.7   302.7  801.24   306.7  800.74
   310.7  800.65   334.5  801.41   338.5  803.67   342.4  807.14   346.4  809.29
   350.4  809.97   374.2  809.86   386.1  813.13     398  814.14   421.9  809.85
   437.7  815.46   445.7  820.19   457.6  830.85   489.4  853.46   521.1  881.34
#Mann= 3 , 0 , 0
       0     .08       0   306.7    .045       0   334.5     .06       0
#XS Ineff= 2 , 0
                          394.33          832.53
Permanent Ineff=
       F       F
Bank Sta=306.7,334.5
XS Rating Curve= 0 ,0
Exp/Cntr=0.3,0.1