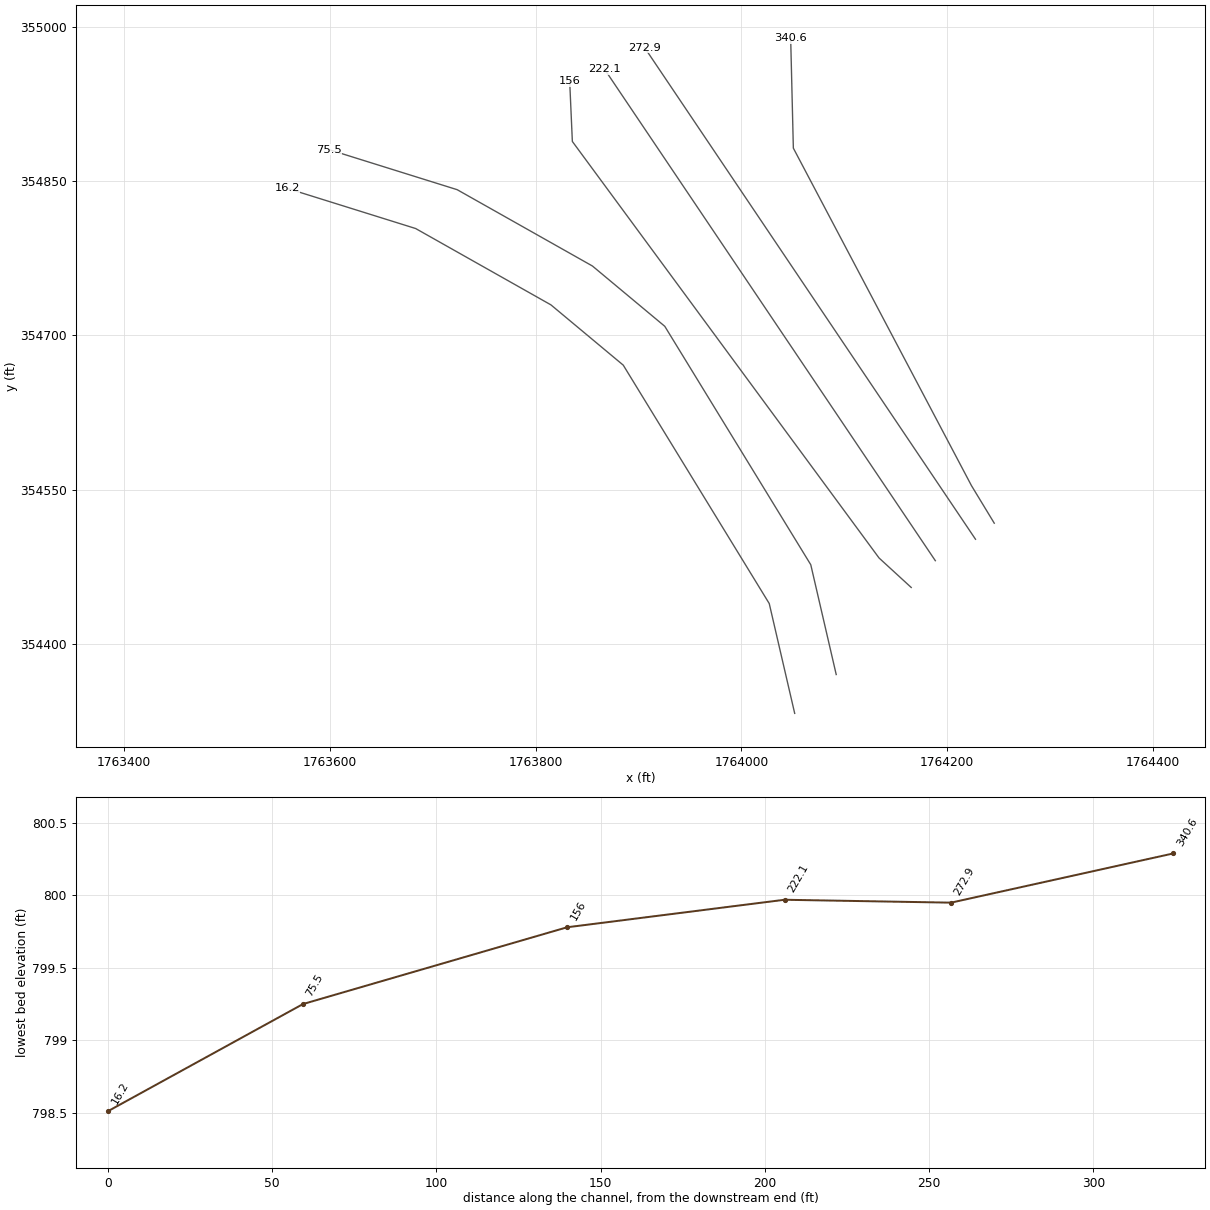
HEC-RAS study WESTFK.prj: WESTFK

--- WESTFK.g01 (geometry) --- (continued)

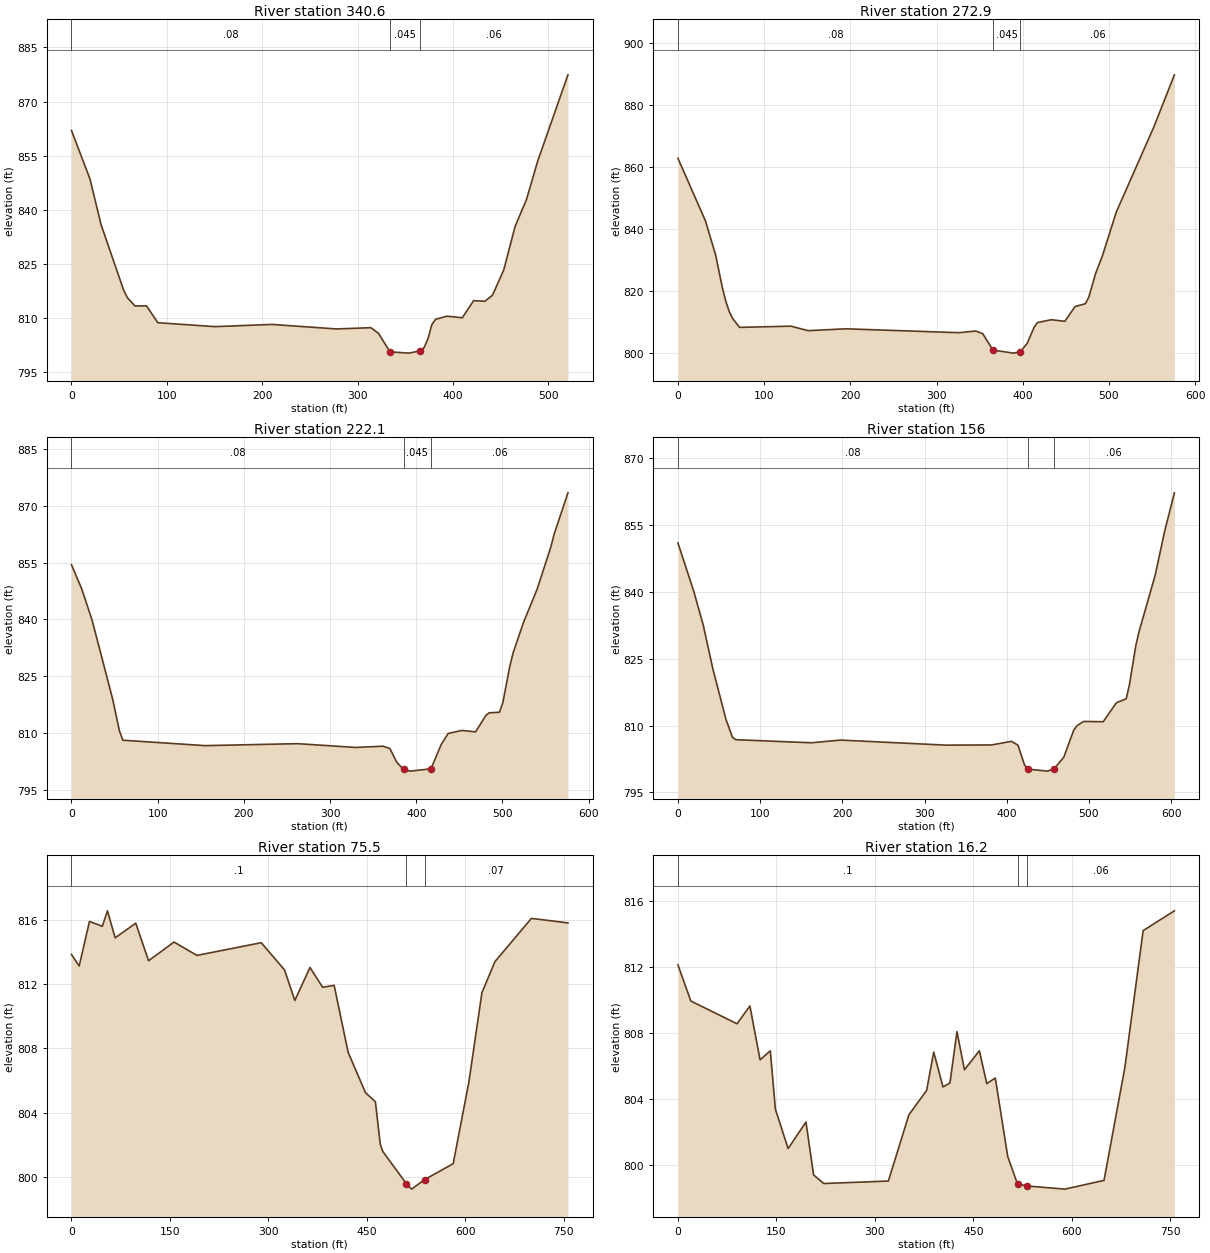
Type RM Length L Ch R = 1 ,340.6   ,63.6,67.7,70.4
XS GIS Cut Line= 4
     1764245.747      354517.393     1764223.612      354553.851
     1764050.435      354881.976     1764047.831      354988.747
#Sta/Elev= 30
       0  861.98    19.4  848.54      31   835.9    54.6   817.8    58.6  815.66
    66.6  813.35    78.6   813.4    90.5  808.72   150.4  807.63   210.2  808.24
     278  806.99   313.9  807.34   321.9  805.77   333.9  800.64   353.8  800.29
   365.8  800.93   369.8  801.86   373.8  804.33   377.8  808.19   381.8  809.67
   393.7  810.53   409.7  810.08   421.6  814.82   433.4  814.66   441.4  816.34
   453.2  823.34   465.1   835.4     477  842.84   488.8   853.5   520.5   877.4
#Mann= 3 , 0 , 0
       0     .08       0   333.9    .045       0   365.8     .06       0
Bank Sta=333.9,365.8
XS Rating Curve= 0 ,0
Exp/Cntr=0.3,0.1

Type RM Length L Ch R = 1 ,272.9   ,51.4,50.7,50.1
XS GIS Cut Line= 2
     1764227.518      354501.768     1763905.904      354979.633
#Sta/Elev= 30
       0  862.74    31.8  842.64    43.7  831.62    51.6  820.96    55.6  816.62
    59.6  813.27    63.6  811.07    71.5  808.25   131.1  808.64     151  807.19
   194.6  807.79   325.8  806.54   345.6  807.07   353.6  806.22   365.5  800.93
   389.3  799.95   397.2  800.36   405.2   803.1   413.1   808.2   417.1   809.8
     433  810.71   448.9  810.21   460.8  814.97   472.7  815.88   476.7  818.01
   484.6  825.62   492.6  831.41   508.5  845.38   552.2  872.88     576  889.65
#Mann= 3 , 0 , 0
       0     .08       0   365.5    .045       0   397.2     .06       0
Bank Sta=365.5,397.2
XS Rating Curve= 0 ,0
Exp/Cntr=0.3,0.1

Type RM Length L Ch R = 1 ,222.1   ,65.9,66.2,67.4
XS GIS Cut Line= 2
     1764188.456      354480.935     1763866.841      354958.799
#Sta/Elev= 30
       0  854.45    11.9  848.07    23.8  839.91    47.7  819.05    55.6  810.61
    59.6  808.13   154.9   806.7   262.2  807.22   329.7  806.22   361.5  806.55
   369.4  805.92   377.4  802.32   385.3  800.42   393.3  799.97   417.1  800.59
     429  807.02     437  809.91   452.9  810.71   468.8  810.34   480.7  814.63
   484.6  815.36   496.6  815.52   500.5  818.07   508.5  827.61   512.4   831.2
   524.4  839.21   540.3  848.03   556.2  859.17   560.1  862.62     576  873.44
#Mann= 3 , 0 , 0
       0     .08       0   385.3    .045       0   417.1     .06       0
Bank Sta=385.3,417.1
XS Rating Curve= 0 ,0
Exp/Cntr=0.3,0.1

Type RM Length L Ch R = 1 ,156     ,65.4,80.4,90.4
XS GIS Cut Line= 4
     1764165.018      354454.893     1764133.768      354483.539
     1763835.591      354888.487     1763832.987      354947.081
#Sta/Elev= 30
       0  850.95    19.3  840.06    30.8   832.5    42.4  822.76    58.4  811.38
    66.3  807.37    70.3  806.83   162.1  806.14     198  806.74   325.8  805.61
   381.6  805.65   405.6  806.46   413.6   805.6   421.6  801.16   425.5  800.23
   449.5  799.78   457.5  800.29   469.4  802.92   481.4  808.95   485.4  809.97
   493.4  810.92   517.3  810.86   533.3  815.11   545.3  816.02   549.2  819.16
     557  827.97   560.9  831.07   580.5  843.71   592.2  853.71   603.9  862.19
#Mann= 3 , 0 , 0
       0     .08       0   425.5    .045       0   457.5     .06       0
Bank Sta=425.5,457.5
XS Rating Curve= 0 ,0
Exp/Cntr=0.3,0.1

Type RM Length L Ch R = 1 ,75.5    ,64.6,59.4,58.1
XS GIS Cut Line= 6
     1764092.102      354370.258     1764067.362      354477.029
     1763925.435      354708.799     1763855.122      354767.393
     1763723.612      354841.612     1763598.612      354880.674
#Sta/Elev= 30
       0  813.83    11.7  813.11    27.4  815.88      47  815.58    54.8  816.54
    66.5  814.86    97.9  815.77   117.4  813.44   156.2   814.6   191.1  813.77
     289  814.56   324.5  812.87   340.2  810.97   363.3  813.02   382.6  811.79
   400.1  811.91   421.4  807.75   447.7  805.25   462.9  804.68   470.4  802.02
   474.2  801.59   510.1  799.59   518.1  799.25   537.8  799.84   581.4  800.83
   605.3   805.9   625.2  811.46   645.1  813.39   700.6  816.07   756.2  815.79
#Mann= 3 , 0 , 0
       0      .1       0   510.1    .045       0   537.8     .07       0
Bank Sta=510.1,537.8
XS Rating Curve= 0 ,0
Exp/Cntr=0.3,0.1

Type RM Length L Ch R = 1 ,16.2    ,26.4,16.2,5.6
XS GIS Cut Line= 6
     1764051.737      354332.497     1764026.997      354439.268
      1763885.07      354671.039     1763814.758      354729.633
     1763683.247      354803.851     1763558.247      354842.914
#Sta/Elev= 30
       0  812.11    19.6  809.92      90  808.54   109.6  809.62   125.1  806.35
   140.7   806.9   148.4  803.36   167.8  800.97     195  802.58   206.6  799.37
   222.2  798.85   320.5     799   351.8  803.02   378.8   804.5   389.6  806.82
   403.7  804.71   414.3  804.95     425  808.06   436.4  805.75   459.1   806.9
   470.4  804.91   483.4  805.25   502.3  800.49   517.2  798.82   532.2   798.7
   589.3  798.51     649  799.04   680.8   805.9   708.6  814.19   756.2  815.39
#Mann= 3 , 0 , 0
       0      .1       0   517.2    .045       0   532.2     .06       0
Bank Sta=517.2,532.2
XS Rating Curve= 0 ,0
Exp/Cntr=0.3,0.1

Chan Stop Cuts=-1
Use User Specified Reach Order=0
Composite Channel Slope=5